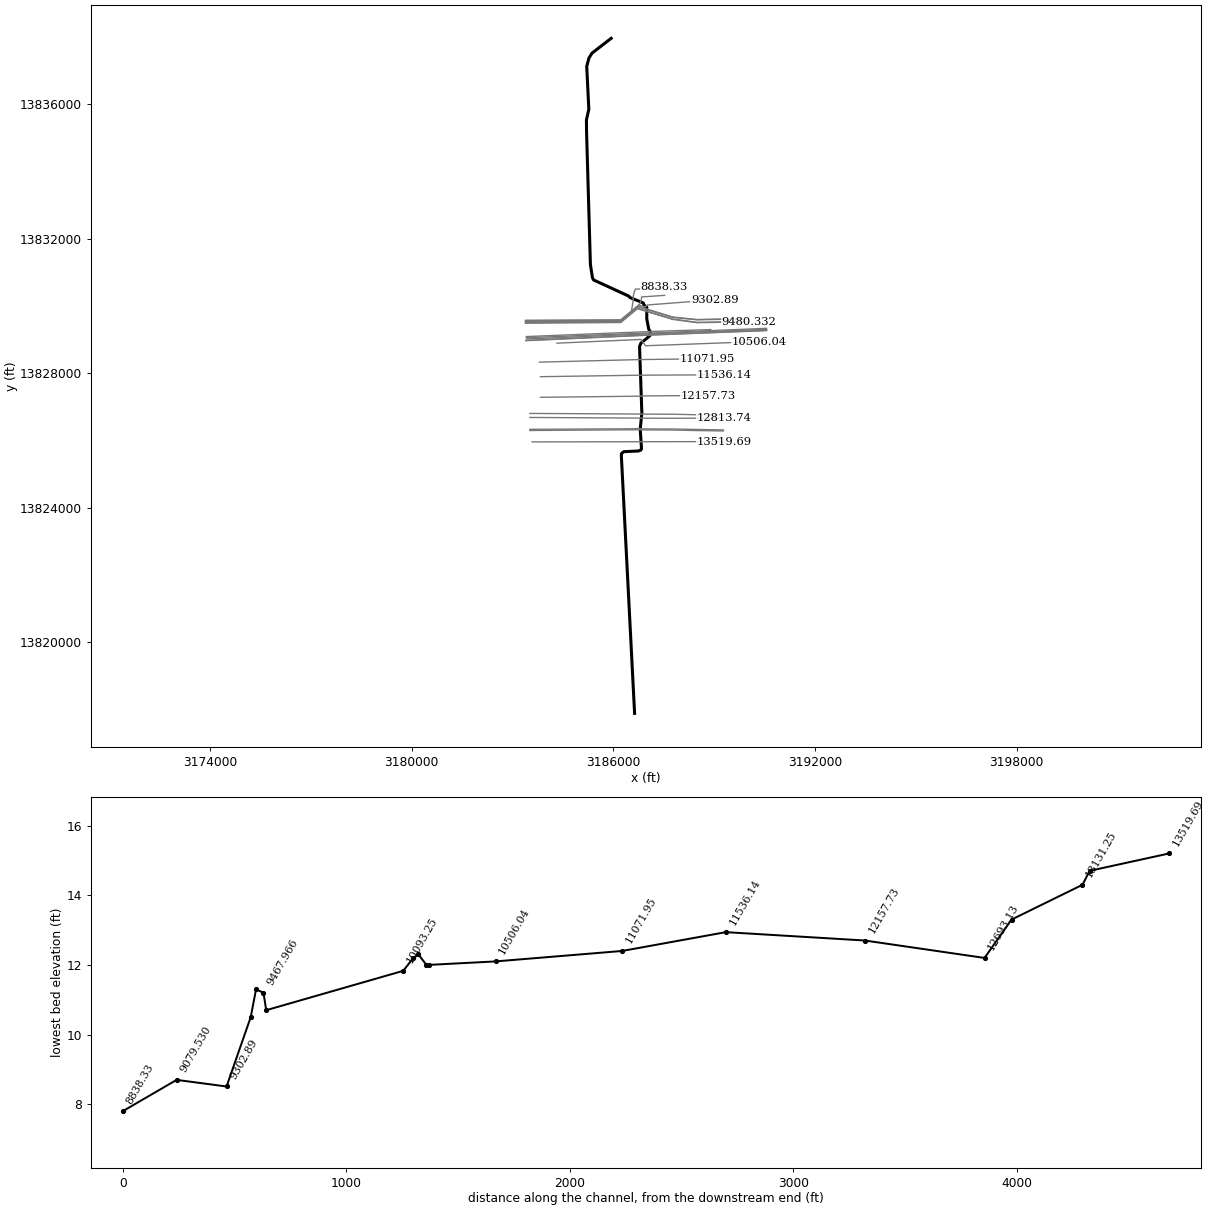
--- G108-00-00.prj (project) ---

Proj Title=G108-00-00
Current Plan=p03
Default Exp/Contr=.3,.1
English Units
Geom File=g01
Flow File=f03
Flow File=f01
Plan File=p04
Plan File=p03
Y Axis Title=Elevation
X Axis Title(PF)=Main Channel Distance
X Axis Title(XS)=Station
BEGIN DESCRIPTION:
San Jacinto
Glenmore Ditch
HCFCD Unit G108-00-00
Flood Hazard Model
10, 2, 1, 0.2% Event
Filename G108_00_00.prj
Prepared by: Matthew Fischer Date: 5-25-04
Updated by: Carl Ahrendt P.E. Date: April 2012
Reviewd by:		Date:
Status Final Submittal
END DESCRIPTION:
DSS Export Rating Curves= 0
DSS Export Rating Curve Sorted= 0
DSS Export Volume Flow Curves= 0
DXF OffsetX= 0
DXF OffsetY= 0
DXF ScaleX= 1
DXF ScaleY= 10

--- G108-00-00.p03 (plan) ---

Plan Title=Effective MP 2013
Version=Version 3.0.1  May 2012
Short Identifier=Eff+LOMR MP
Geom File=g01
Flow File=f01
Subcritical Flow
K Sum by GR= 0
Std Step Tol= 0.003
Critical Tol= 0.003
Num of Std Step Trials= 20
Max Error Tol= 0.1
Flow Tol Ratio= 0.001
Split Flow NTrial= 30
Split Flow Tol= 0.02
Split Flow Ratio= 0.02
Log Output Level= 0
Friction Slope Method= 0
Unsteady Friction Slope Method= 2
Secant Critical Depth
Global Vel Dist= 0 , 0 , 0
Global Log Level= 0
CheckData=True
Encroach Param=-1 ,0,0, 0
BEGIN DESCRIPTION:
FEMA Effective Multi-Profile 2007 + LOMR 12-06-3062 + LOMR 13-06-0356P
END DESCRIPTION:
Computation Interval=1HOUR
Output Interval=1HOUR
Run HTab= 0
Run UNet= 0
Run PostProcess= 0
UNET Theta= 1
UNET ZTol= 0.02
UNET ZSATol= 0.1
UNET MxIter= 20
UNET MaxInSteps= 20
UNET DtIC= 0
UNET DtMin= 0
UNET MaxCRTS= 20
UNET WFStab= 2
UNET SFStab= 1
UNET WFX= 1
UNET SFX= 1
UNET Convert EG Bridges=-1
UNET Use Existing IB Tables=-1
Instantaneous Interval=1HOUR
DSS File=dss
Write IC File= 0
IC Time=0
Write Velocity= 0
Write Detailed= 0

--- G108-00-00.p04 (plan) ---

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Plan Title=Effective FW 2013
Short Identifier=Eff+LOMR FW
Geom File=g01
Flow File=f03
Encroach Param=-1 ,0,0, 2
Encroach River=G108-00-00
Encroach Reach=G108-00-00_0011
Encroach Node=13519.69
       1 4963.79 5038.67
Encroach Node=13163.27
       1 4969.22 5042.75
Encroach Node=13131.25
       1 4946.04 5060.95
Encroach Node=12972
       1 4946.04 5060.95
Encroach Node=12813.74
       1 4956.56  5030.4
Encroach Node=12693.13
       1 4956.01 5041.39
Encroach Node=12157.73
       1 4968.72 5052.04
Encroach Node=11536.14
       1 4960.98  5039.3
Encroach Node=11071.95
       1 4957.74 5043.34
Encroach Node=10506.04
       1 4965.91 5047.13
Encroach Node=10207.03
       1 4979.98 5029.06
Encroach Node=10197.03
       1 4979.98 5029.06
Encroach Node=10189.03
       1 4965.17 5036.34
Encroach Node=10160.80
       1 4971.96 5033.44
Encroach Node=10138.08
       1 4972.02 5045.55
Encroach Node=10093.25
       1 4950.56 5019.22
Encroach Node=9480.332
       1 4847.08 5147.08
Encroach Node=9467.966
       1 4974.28 5028.75
Encroach Node=9450
       1 4974.28 5028.75
Encroach Node=9434.832
       1 4973.47 5020.26
Encroach Node=9410.90
       1 4941.17 5029.17
Encroach Node=9302.89
       1 4904.85 5099.85
Encroach Node=9079.530
       1 4787.83    5209
Encroach Node=8838.33
       1 4949.11 5043.08
Encroach Node=8812
       1 4949.11 5048.09
Encroach Node=8778.77
       1 4952.52 5048.09
Encroach Node=8728.080
       1 4950.73 5036.07
Encroach Node=8200.56
       1 4948.34 5033.76
Encroach Node=7648.81
       1  4949.8  5042.7
Encroach Node=7527.599
       1 4915.85 5056.05
Encroach Node=7485.81
       1 4915.85 5056.05
Encroach Node=7445.585
       1  4946.3  5048.3
Encroach Node=7417.47
       1  4945.2 5051.67
Encroach Node=6381.43
       1  4954.6 5053.32
Encroach Node=5931.941
       1  4946.3  5054.5
Encroach Node=5353.325
       1 4929.08 5052.41
Encroach Node=4827.405
       1 4939.95 5060.57
Encroach Node=3196.063
       1 4947.34 5052.66
Encroach Node=3156.096
       1 4937.24 5095.31
Encroach Node=3126
       1 4937.24 5095.31
Encroach Node=3096.103
       1 4928.15 5081.45
Encroach Node=2932.802
       1 4952.75 5066.72
Encroach Node=1897.854
       1 4965.32  5058.6
Encroach Node=1148.744
       1 4967.98 5032.02
Encroach Node=1074.414
       1 4907.64 4983.55
Encroach Node=1071
       1 4907.64 4983.55
Encroach Node=1068.958
       1 4907.64 4983.55
FEMA Effective Floodway 2007 + LOMR 12-06-3062 + LOMR 13-06-0356P

--- G108-00-00.f01 (steady flow) ---

Flow Title=Effective MP 2013
Version=Version 3.0.1  Mar 2001
Number of Profiles= 4
Profile Names=10PCT_10yr,2PCT_50yr,1PCT_100yr,0.2PCT_500yr
River Rch & RM=G108-00-00,G108-00-00_0011 ,13519.69
  1505.3  2083.2    2323  2939.4
River Rch & RM=G108-00-00,G108-00-00_0011 ,12693.13
 1575.38 2171.57 2420.09  3051.9
River Rch & RM=G108-00-00,G108-00-00_0011 ,11536.14
 1678.99  2301.6 2562.85 3216.63
River Rch & RM=G108-00-00,G108-00-00_0011 ,10207.03
 1806.45 2460.62 2737.26 3416.88
River Rch & RM=G108-00-00,G108-00-00_0011 ,9434.832
  2060.2  2796.8  3124.9  3904.6
River Rch & RM=G108-00-00,G108-00-00_0011 ,5353.325
 2134.42 2913.06 3264.15 4096.92
Boundary for River Rch & Prof#=G108-00-00,G108-00-00_0011 , 1
Up Type= 0
Dn Type= 1
Dn Known WS=1.5
DSS Import GetInterval= 0
DSS Import GetPeak= 0
DSS Import FillOption= 0

--- G108-00-00.f03 (steady flow) ---

Flow Title=Effective FW 2013
Version=Version 3.0.1  Mar 2001
Number of Profiles= 2
Profile Names=1PCT_100yr,1PCTFloodway_100yr
River Rch & RM=G108-00-00,G108-00-00_0011 ,13519.69
    2323    2323
River Rch & RM=G108-00-00,G108-00-00_0011 ,12693.13
 2420.09 2420.09
River Rch & RM=G108-00-00,G108-00-00_0011 ,11536.14
 2562.85 2562.85
River Rch & RM=G108-00-00,G108-00-00_0011 ,10207.03
 2737.26 2737.26
River Rch & RM=G108-00-00,G108-00-00_0011 ,9434.832
  3124.9  3124.9
River Rch & RM=G108-00-00,G108-00-00_0011 ,5353.325
 3264.15 3264.15
Boundary for River Rch & Prof#=G108-00-00,G108-00-00_0011 , 1
Up Type= 0
Dn Type= 1
Dn Known WS=1.5
Boundary for River Rch & Prof#=G108-00-00,G108-00-00_0011 , 2
Up Type= 0
Dn Type= 1
Dn Known WS=2.5
DSS Import GetInterval= 0
DSS Import GetPeak= 0
DSS Import FillOption= 0

--- G108-00-00.g01 (geometry) ---

Geom Title=G108-00-00 2013
Version=Version 3.0.1  May 2012

River Reach=G108-00-00      ,G108-00-00_0011
Reach XY= 30
     3186634.553    13817887.788       3186239.5       13825570.
      3186247.25       13825618.     3186313.408     13825670.63
     3186748.872    13825690.739       3186822.5       13825719.
      3186839.75       13825765.     3186801.331    13826342.299
     3186850.213    13826815.619     3186782.017    13828796.874
       3186819.5       13828895.       3187086.5       13829115.
       3187107.5       13829231.      3187057.25       13829307.
        3186997.       13829615.        3186997.       13829961.
      3186915.75       13830027.      3186888.75       13830096.
     3186498.286    13830253.238        3186462.       13830296.
      3185414.25       13830778.      3185381.25       13830844.
       3185320.5       13831235.       3185206.5       13835157.
        3185202.       13835534.      3185273.25       13835857.
       3185210.5       13837127.      3185275.75       13837374.
       3185366.5       13837522.       3185936.5       13837963.

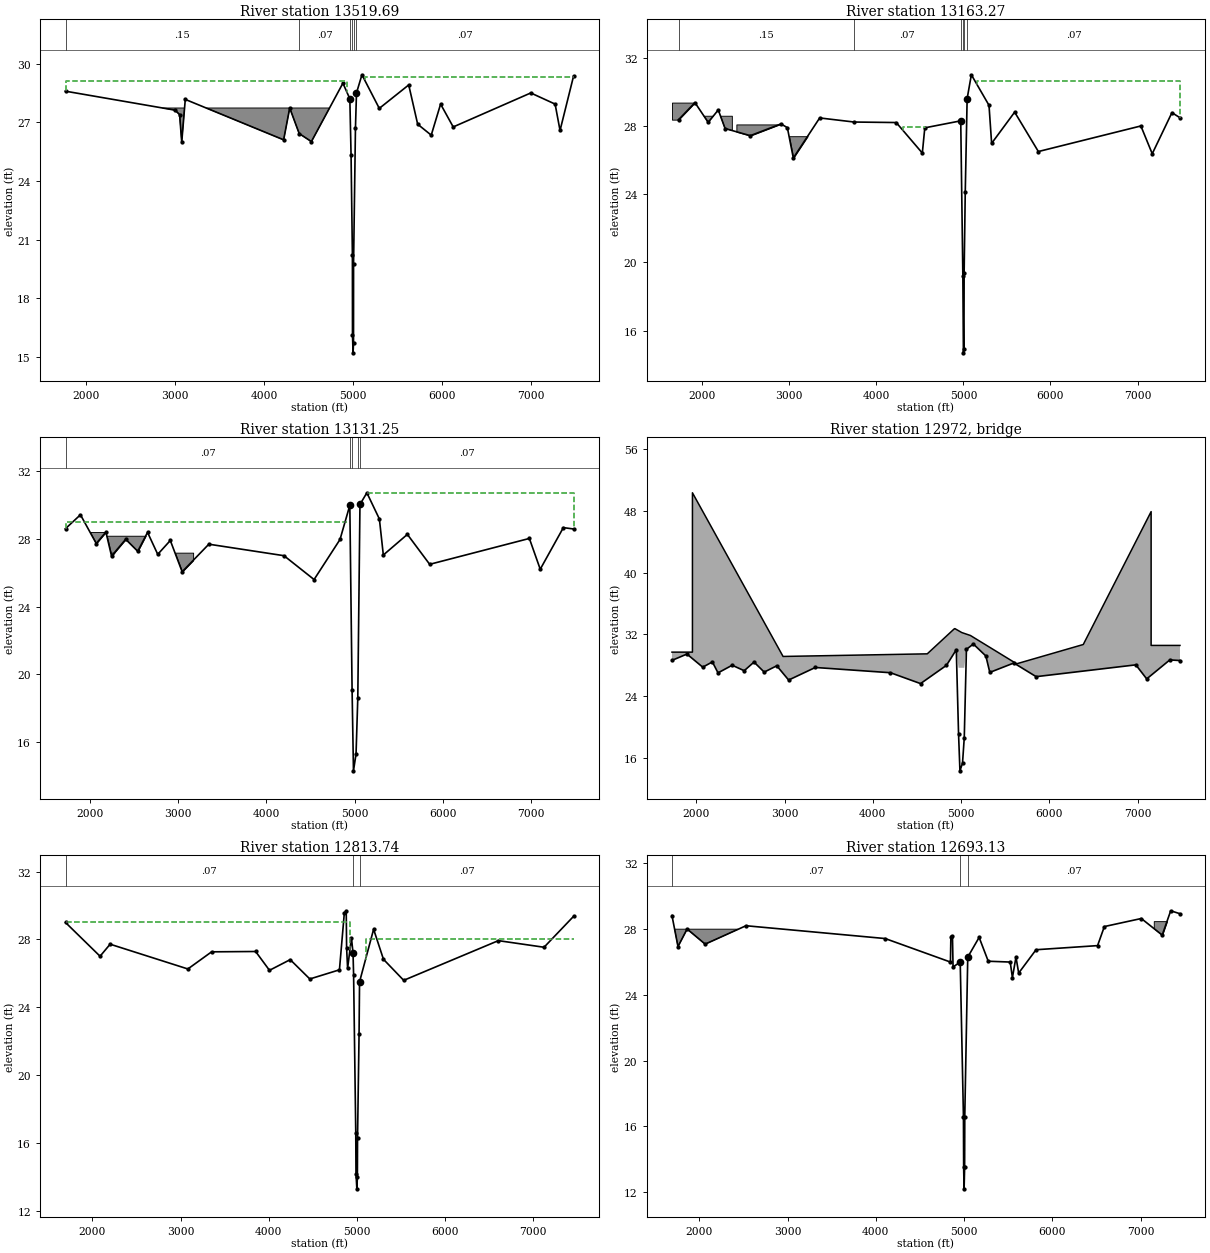
Type RM Length L Ch R = 1 ,13519.69,356.42,356.42,356.42
BEGIN DESCRIPTION:
Cross Section updated by Carl Ahrendt, P.E., April 2012
END DESCRIPTION:
XS GIS Cut Line= 2
      3183587.48    13825961.283     3189301.197    13825970.455
#Sta/Elev= 30
 1766.03   28.59 2997.92   27.62 3049.24   27.39 3073.18   25.98 3113.05   28.17
 4219.41    26.1 4287.66   27.73 4394.34   26.42 4531.52   26.01 4885.98      29
 4963.79    28.2  4977.6    25.3 4992.62    20.2 4993.63   16.12    5000    15.2
 5005.16   15.68 5005.68   19.76 5026.93    26.7 5038.67    28.5    5100   29.43
 5295.03   27.71 5626.05   28.91 5726.68    26.9 5879.15   26.34 5984.59   27.93
 6126.27   26.76 6998.63    28.5  7272.4   27.93 7327.85   26.58 7479.75   29.36
#Mann= 6 ,-1 , 0
 1766.03     .15       0 4394.34     .07       0 4963.79     .03       0
 4992.62    .015       0 5005.68     .03       0 5038.67     .07       0
#XS Ineff= 2 , 0
       0 4935.36    29.1    5129       0   29.33
Permanent Ineff=
       F       F
#Block Obstruct= 2 , 0
       0    4730   27.73    5626       0      28
Bank Sta=4963.79,5038.67
XS Rating Curve= 0
Exp/Cntr=.3,.1

Type RM Length L Ch R = 1 ,13163.27,32.02,32.02,32.02
BEGIN DESCRIPTION:
LaPorte Freeway
Cross Section updated by Carl Ahrendt, P.E., April 2012
END DESCRIPTION:
XS GIS Cut Line= 6
      3183519.67     13826300.71     3186712.528    13826321.983
     3187054.253    13826316.685     3187797.448    13826314.003
     3188511.205    13826297.903      3189278.34    13826287.601
#Sta/Elev= 30
 1728.83   28.37  1916.2   29.37 2068.48   28.21 2184.25   28.94 2262.27   27.85
 2551.97   27.43 2904.59   28.12 2977.81    27.9 3046.24   26.12 3349.01   28.47
 3744.51   28.23 4228.49    28.2 4528.04   26.41  4556.4   27.89 4969.22    28.3
 4993.62    19.2    5000    14.7 5006.16   14.93 5008.27    19.4 5020.98    24.1
 5042.75    29.6 5091.21      31 5293.96   29.21 5323.96   26.98 5588.49   28.81
 5860.79    26.5 7038.37      28 7168.93   26.37 7395.19   28.78 7487.93   28.48
#Mann= 6 ,-1 , 0
 1728.83     .15       0 3744.51     .07       0 4969.22     .03       0
 4993.62    .015       0 5008.27     .03       0 5042.75     .07       0
#XS Ineff= 2 ,-1
 4310.66 4561.13   27.91 5161.14 7487.93   30.64
Permanent Ineff=
       F       F
#Block Obstruct= 4 ,-1
 1652.38 1916.06   29.37 1828.21 2345.85   28.57 2392.11 2902.63   28.09
 2982.47 3221.71    27.4
Bank Sta=4969.22,5042.75
XS Rating Curve= 0
Exp/Cntr=.5,.3

Type RM Length L Ch R = 1 ,13131.25,317.51,317.51,317.51
BEGIN DESCRIPTION:
LaPorte Freeway
Cross Section updated by Carl Ahrendt, P.E., April 2012
END DESCRIPTION:
XS GIS Cut Line= 6
     3183521.853    13826335.524     3186632.636     13826352.51
     3186710.518    13826357.952     3186886.434    13826348.886
     3187797.858    13826344.001     3189278.331    13826317.604
#Sta/Elev= 30
 1724.14   28.62  1893.6   29.44 2072.68   27.74 2181.92   28.42 2245.85      27
 2406.24   27.99 2542.65   27.28 2653.75    28.4 2769.36    27.1 2911.79   27.92
 3045.97   26.07 3348.46    27.7 4200.01   27.02 4541.03   25.61 4834.97   27.98
 4946.04      30 4971.66    19.1  4987.4    14.3 5016.59    15.3 5036.39    18.6
 5060.95   30.05 5139.31   30.74 5281.11   29.19 5325.78   27.06 5598.17   28.28
 5851.02   26.51 6980.66   28.04 7103.88   26.22  7365.9   28.68 7481.36    28.6
#Mann= 5 ,-1 , 0
 1724.14     .07       0 4946.04     .03       0 4971.66    .015       0
 5036.39     .03       0 5060.95     .07       0
#XS Ineff= 2 , 0
       0    4915      29 5139.31       0   30.74
Permanent Ineff=
       F       F
#Block Obstruct= 4 ,-1
 1935.32 2178.99   28.42 2180.81    2655    28.2    2200    2300    27.2
 2895.02 3170.28    27.2
Bank Sta=4946.04,5060.95
XS Rating Curve= 0
Exp/Cntr=.5,.3

Type RM Length L Ch R = 3 ,12972   ,,,
BEGIN DESCRIPTION:
Bridge at Laporte Freeway
END DESCRIPTION:
Bridge Culvert--1,0,-1,-1, 0
Deck Dist Width WeirC Skew NumUp NumDn MinLoCord MaxHiCord MaxSubmerge Is_Ogee
8,276,2.6,0, 14, 13, , , .95, 0, 0,0,,
    1724    1956    1956    2983    4617    4922    4930    5008    5106    5630
    6385    7154    7154    7481
   29.69   29.69   50.35   29.13   29.47    32.7   32.74   32.23   31.85   28.18
   30.68   47.91   30.56   30.56
       0       0       0       0       0   27.66   27.66   27.66   27.66       0
       0       0       0       0
    1694    1956    1956    2983    4617    4930    5008    5106    5630    6385
    7154    7154    7457
   29.68   29.68   50.35   29.13   29.47   32.74   32.23   31.85   28.18   30.68
   47.91   30.56   30.56
       0       0       0       0       0   27.66   27.66   27.66       0       0
       0       0       0
BR Coef=-1 , 0 , 0 ,, 0 ,,,.8,-1,,0,
WSPro=,,,, 1 ,,,, 0 ,,,, 0 ,,,,-1 ,-1 ,-1 , 0 , 0 , 0 , 0 , 0
BC Design=,, 0 ,, 0 ,,,,,,
BC HTab HWMax=30.74

Type RM Length L Ch R = 1 ,12813.74,120.61,120.61,120.61
BEGIN DESCRIPTION:
LaPorte Freeway
Cross Section updated by Carl Ahrendt, P.E., April 2012
END DESCRIPTION:
XS GIS Cut Line= 6
     3183521.328    13826688.229     3186896.768    13826668.778
     3187056.545    13826666.685     3187802.232    13826663.984
      3188528.28    13826667.011     3189284.273     13826676.54
#Sta/Elev= 30
 1694.87      29 2086.84   27.01 2201.11   27.72  3082.9   26.26 3352.21   27.27
 3851.56   27.29 4008.65   26.18  4243.9   26.81  4466.4   25.67 4802.29   26.21
 4857.57   29.55 4879.37   29.69 4883.58    27.5 4894.94    26.3 4938.44    28.1
 4956.56    27.2 4962.95    25.9  4987.5    16.6 4989.93    14.2    5000    13.3
 5005.77      14 5007.56    16.3 5024.82    22.4  5030.4    25.5  5189.9    28.6
 5301.71   26.83 5531.14   25.59 6605.11   27.93 7123.21   27.54 7457.96   29.36
#Mann= 3 ,-1 , 0
 1694.87     .07       0 4956.56     .03       0  5030.4     .07       0
#XS Ineff= 2 , 0
       0    4921      29    5098       0      28
Permanent Ineff=
       F       F
Bank Sta=4956.56,5030.4
XS Rating Curve= 0
Exp/Cntr=.5,.3

Type RM Length L Ch R = 1 ,12693.13,535.4,535.4,535.4
BEGIN DESCRIPTION:
LaPorte Freeway
Cross Section updated by Carl Ahrendt, P.E., April 2012
END DESCRIPTION:
XS GIS Cut Line= 6
     3183522.052    13826808.227     3186900.644    13826788.738
     3187057.331    13826786.685     3187803.872    13826783.978
      3188519.66    13826767.832     3189278.187    13826757.645
#Sta/Elev= 30
 1690.03   28.83 1758.24   26.94 1861.72   28.01 2066.26   27.09  2528.6   28.21
 4106.15   27.43 4845.31      26 4850.26   27.55 4868.19   27.57 4874.86    25.7
 4956.01      26 4992.56    16.6 4994.96    13.5    5000    12.2 5005.93    13.5
 5007.66    16.6 5041.39    26.3 5170.31    27.5 5273.78   26.05 5522.68      26
 5547.38   25.05  5587.8    26.3 5618.58   25.33 5815.29   26.75 6512.41      27
 6589.35   28.16 7007.89   28.65 7244.65   27.64 7341.04   29.12 7446.49   28.94
#Mann= 3 ,-1 , 0
 1690.03     .07       0 4956.01     .03       0 5041.39     .07       0
#XS Ineff= 2 , 0
       0 4850.26   27.55 5170.31       0    27.5
Permanent Ineff=
       F       F
#Block Obstruct= 2 ,-1
 1641.86 2433.33      28 7149.12 7309.37   28.49
Bank Sta=4956.01,5041.39
XS Rating Curve= 0
Exp/Cntr=.3,.1

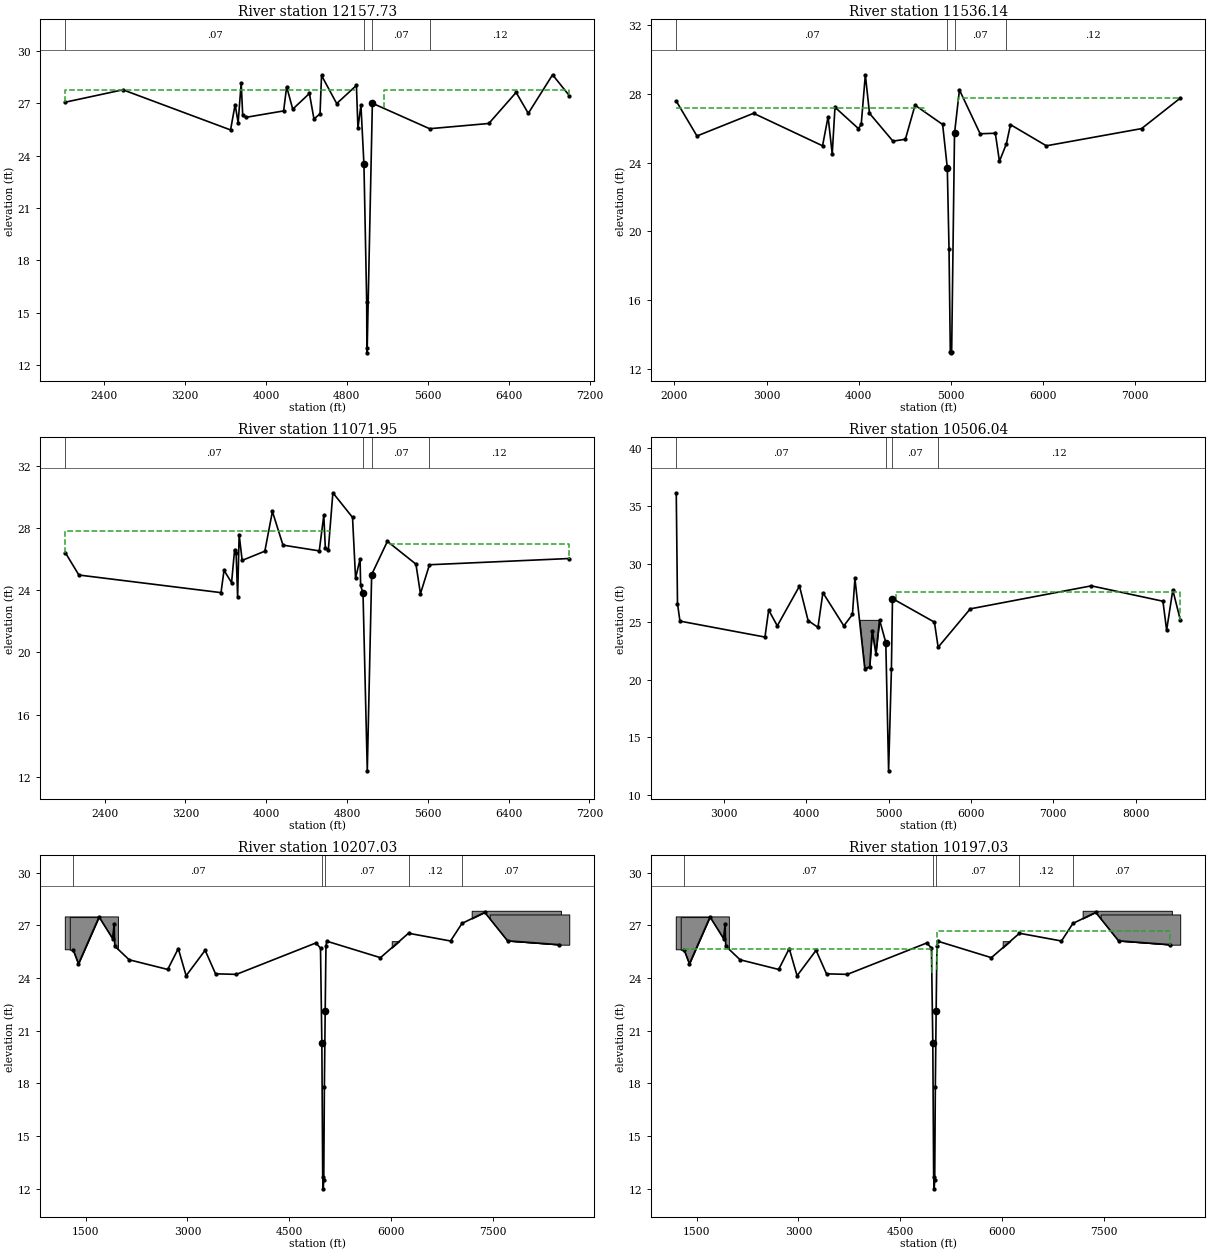
Type RM Length L Ch R = 1 ,12157.73,621.59,621.59,621.59
BEGIN DESCRIPTION:
Cross Section updated by Carl Ahrendt, P.E., April 2012
END DESCRIPTION:
XS GIS Cut Line= 4
 3183836.231311613827287.7717996 3186757.551428813827320.6452416
 3186970.856744713827329.5729438 3188815.666085213827340.2806308
#Sta/Elev= 30
 2017.81   27.06 2587.13   27.77 3650.86   25.47  3695.8   26.92 3725.77   25.89
 3755.73   28.16 3770.71   26.33 3800.68   26.19 4175.23   26.56 4205.19   27.95
 4265.12   26.66 4429.92   27.56 4474.87    26.1  4534.8   26.39 4549.78   28.59
  4699.6   26.98 4894.37   28.02 4909.35   25.57 4938.98    26.9 4968.72    23.5
 4996.03    15.6 4997.77      13    5000    12.7 5052.04      27 5617.77   25.54
 6202.72   25.84 6472.69   27.62 6592.68   26.42 6832.66   28.63 6997.65   27.44
#Mann= 4 ,-1 , 0
 2017.81     .07       0 4968.72     .03       0 5052.04     .07       0
 5617.77     .12       0
#XS Ineff= 2 , 0
       0 4879.39   27.77 5167.81       0   27.73
Permanent Ineff=
       F       F
Bank Sta=4968.72,5052.04
XS Rating Curve= 0
Exp/Cntr=.3,.1

Type RM Length L Ch R = 1 ,11536.14,464.19,464.19,464.19
BEGIN DESCRIPTION:
Cross Section updated by Carl Ahrendt, P.E., April 2012
END DESCRIPTION:
XS GIS Cut Line= 4
 3183834.335520713827900.5060115 3186753.659883513827944.3329707
 3186875.963006713827945.7255661 3189300.883539813827957.1808732
#Sta/Elev= 30
 2020.78   27.58 2245.37   25.55 2859.25   26.87 3607.87   24.98 3667.76   26.67
 3712.68    24.5 3742.63   27.22 3997.16   25.98  4027.1   26.22 4072.02   29.11
 4116.94   26.87 4371.47   25.25 4506.23   25.36 4611.04   27.34 4910.49   26.22
 4960.98    23.7 4979.66      19 4993.62      13    5000   12.94 5008.27      13
  5039.3    25.7 5092.68   28.23 5317.21   25.68 5481.87   25.71 5526.78   24.08
 5601.62   25.09 5646.53   26.21 6035.71   24.98 7068.56   25.98 7487.68   27.75
#Mann= 4 ,-1 , 0
 2020.78     .07       0 4960.98     .03       0  5039.3     .07       0
 5601.62     .12       0
#XS Ineff= 2 , 0
       0 4715.85   27.16 5077.71       0   27.77
Permanent Ineff=
       F       F
Bank Sta=4960.98,5039.3
XS Rating Curve= 0
Exp/Cntr=.3,.1

Type RM Length L Ch R = 1 ,11071.95,622,565.91,535.98
BEGIN DESCRIPTION:
Cross Section updated by Carl Ahrendt, P.E., April 2012
END DESCRIPTION:
XS GIS Cut Line= 4
      3183806.43     13828333.29  3186725.155689 13828407.864974
 3186965.524365213828411.5531973 3188796.034027613828435.6737382
#Sta/Elev= 30
 2010.12   26.41 2144.65   24.97 3551.68   23.84 3581.62   25.27 3656.46   24.48
  3686.4    26.6 3701.37   26.39 3716.34   23.56  3731.3   27.56 3761.24   25.91
 3985.77    26.5 4060.61   29.05 4165.39   26.89 4524.63   26.52 4569.54   28.81
 4584.51   26.72 4614.44    26.6 4659.35   30.25 4853.94   28.67 4883.88   24.77
 4928.78      26 4934.09    24.3 4957.74    23.8    5000    12.4 5043.34      25
 5198.94   27.13 5481.73   25.67 5526.38   23.77 5615.68   25.63 6999.85   26.03
#Mann= 4 ,-1 , 0
 2010.12     .07       0 4957.74     .03       0 5043.34     .07       0
 5615.68     .12       0
#XS Ineff= 2 , 0
       0 4644.38   27.77 5213.83       0   26.98
Permanent Ineff=
       F       F
Bank Sta=4957.74,5043.34
XS Rating Curve= 0
Exp/Cntr=.3,.1

Type RM Length L Ch R = 1 ,10506.04,214.19,299.01,336.78
BEGIN DESCRIPTION:
Cross Section updated by Carl Ahrendt, P.E., April 2012
END DESCRIPTION:
XS GIS Cut Line= 4
       3184326.2     13828897.73 3186822.721840313829007.9530379
 3186958.1649297 13828820.481936 3190344.156427813828945.4108446
#Sta/Elev= 30
 2422.38   36.15 2437.34   26.57 2467.25   25.05 3499.28   23.67 3544.15   26.01
 3648.85   24.64 3918.08   28.08 4022.78    25.1 4142.43   24.51 4202.26   27.51
 4456.53   24.64 4561.23   25.63 4591.14   28.75  4710.8   20.93 4770.63    21.1
 4800.54   24.19 4845.41   22.23 4890.28   25.16 4965.91    23.2    5000    12.1
 5034.08    20.9 5047.13      27 5556.27   24.96 5601.25   22.79 5991.05   26.11
 7460.31    28.1 8329.88   26.77 8374.85   24.27 8449.82   27.74 8539.77   25.18
#Mann= 4 ,-1 , 0
 2422.38     .07       0 4965.91     .03       0 5047.13     .07       0
 5601.25     .12       0
#XS Ineff= 2 , 0
       0 4591.14   28.75 5086.92       0    27.6
Permanent Ineff=
       F       F
#Block Obstruct= 1 ,-1
 4636.01 4890.28   25.16
Bank Sta=4965.91,5047.13
XS Rating Curve= 0
Exp/Cntr=.3,.1

Type RM Length L Ch R = 1 ,10207.03,10,10,10
BEGIN DESCRIPTION:
Access Road
Cross Section updated by Carl Ahrendt, P.E., April 2012
END DESCRIPTION:
XS GIS Cut Line= 6
 3183399.308736513828971.7657487 3187000.087736513829133.4807487
 3187048.432736513829132.6417487 3187146.264736513829140.5847487
 3187176.518736513829140.0617487 3190555.711736513829271.2537487
#Sta/Elev= 30
 1314.67   25.61 1393.09   24.81 1696.69   27.48    1898   26.24 1918.93    27.1
 1927.67   25.82 2140.53   25.04 2708.51   24.49 2864.44   25.68  2979.7   24.13
 3259.91   25.58 3413.43   24.24 3720.74   24.21 4893.65      26 4960.06    25.7
 4979.98    20.3 4992.36    12.7    5000      12 5008.16    12.5 5017.25    17.8
 5029.06    22.1 5040.48    25.8 5051.52    26.1 5843.38   25.16 6257.09   26.55
 6876.16   26.11 7045.02   27.11 7380.54   27.74  7716.9   26.12  8477.6    25.9
#Mann= 5 ,-1 , 0
 1314.67     .07       0 4979.98     .03       0 5029.06     .07       0
 6257.09     .12       0 7045.02     .07       0
#Block Obstruct= 6 ,-1
  1199.2    1982   27.48 1264.74 1693.96   27.47 6009.79 6260.27    26.1
    7188 8502.84   27.83 7205.79 7276.66   27.03 7453.78 8626.07   27.62
Bank Sta=4979.98,5029.06
XS Rating Curve= 0
Exp/Cntr=.5,.3

Type RM Length L Ch R = 1 ,10197.03,36.23,36.23,36.23
BEGIN DESCRIPTION:
Access Road
Cross Section updated by Carl Ahrendt, P.E., April 2012
END DESCRIPTION:
XS GIS Cut Line= 6
     3183405.974    13828978.984     3187006.753    13829140.699
     3187055.098     13829139.86      3187152.93    13829147.803
     3187183.184     13829147.28     3190562.377    13829278.472
#Sta/Elev= 30
 1314.67   25.61 1393.09   24.81 1696.69   27.48    1898   26.24 1918.93    27.1
 1927.67   25.82 2140.53   25.04 2708.51   24.49 2864.44   25.68  2979.7   24.13
 3259.91   25.58 3413.43   24.24 3720.74   24.21 4893.65      26 4960.06    25.7
 4979.98    20.3 4992.36    12.7    5000      12 5008.16    12.5 5017.25    17.8
 5029.06    22.1 5040.48    25.8 5051.52    26.1 5843.38   25.16 6257.09   26.55
 6876.16   26.11 7045.02   27.11 7380.54   27.74  7716.9   26.12  8477.6    25.9
#Mann= 5 ,-1 , 0
 1314.67     .07       0 4979.98     .03       0 5029.06     .07       0
 6257.09     .12       0 7045.02     .07       0
#XS Ineff= 2 , 0
       0 4965.17   25.68 5036.34       0   26.68
Permanent Ineff=
       F       F
#Block Obstruct= 6 ,-1
  1199.2    1982   27.48 1264.74 1693.96   27.47 6009.79 6260.27    26.1
    7188 8502.84   27.83 7205.79 7276.66   27.03 7453.78 8626.07   27.62
Bank Sta=4979.98,5029.06
XS Rating Curve= 0
Exp/Cntr=.5,.3

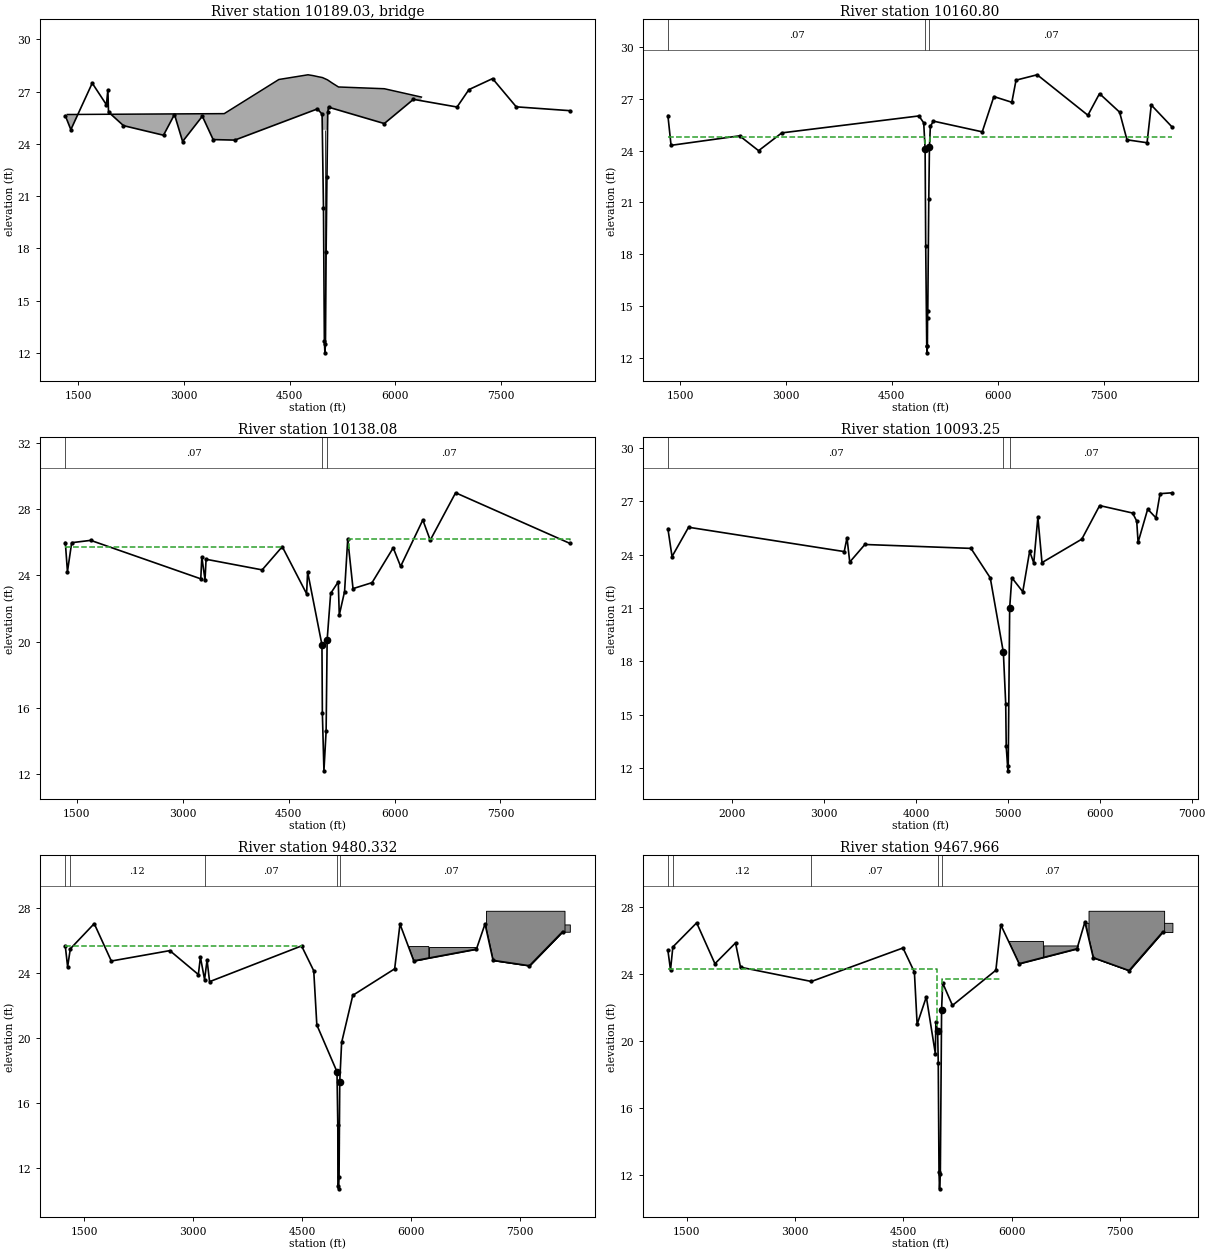
Type RM Length L Ch R = 3 ,10189.03,,,
BEGIN DESCRIPTION:
Bridge at Access Road
END DESCRIPTION:
Bridge Culvert--1,0,-1,-1, 0
Deck Dist Width WeirC Skew NumUp NumDn MinLoCord MaxHiCord MaxSubmerge Is_Ogee
2,30,2.6,0, 14, 14, , , .95, 0, 0,0,,
 1343.27 3570.59  4346.3 4760.25 4835.45 4903.19 4965.17 4965.17 5036.34 5036.34
 5106.22 5192.95 5843.38 6370.55
   25.68   25.73   27.69   27.96   27.91   27.85    27.8    27.8   27.67   27.67
   27.48   27.26   27.16   26.68
       0       0       0       0       0       0       0    24.8    24.8       0
       0       0       0       0
 1343.27 3570.59  4346.3 4760.25 4835.45 4903.19 4965.17 4965.17 5036.34 5036.34
 5106.22 5192.95 5843.38 6370.55
   25.68   25.73   27.69   27.96   27.91   27.85    27.8    27.8   27.67   27.67
   27.48   27.26   27.16   26.68
       0       0       0       0       0       0       0    24.8    24.8       0
       0       0       0       0
Pier Skew, UpSta & Num, DnSta & Num=  ,5000, 4 ,5000, 4 , 3 , 3 , 0 ,,
    1.75    1.75       2       2
       0   23.41   23.41      25
    1.75    1.75       2       2
       0   23.41   23.41      25
BR Coef=-1 , 0 , 0 ,, 0 ,,,.8,-1,2,0,
WSPro=,,,, 1 ,,,, 0 ,,,, 0 ,,,,-1 ,-1 ,-1 , 0 , 0 , 0 , 0 , 0
BC Design=,, 0 ,, 0 ,,,,,,
BC HTab HWMax=27.74

Type RM Length L Ch R = 1 ,10160.80,22.72,22.72,22.72
BEGIN DESCRIPTION:
Cross Section updated by Carl Ahrendt, P.E., April 2012
END DESCRIPTION:
XS GIS Cut Line= 4
 3183419.317025313829022.4648335 3186852.134874813829167.1794896
 3187285.301319113829184.9209434 3190560.521392713829307.1658404
#Sta/Elev= 30
 1328.33   26.02 1373.15    24.3 2344.15   24.85 2613.05   23.99 2941.69   25.02
 4884.52      26 4952.07    25.6 4971.96    24.1 4980.45    18.5 4995.01    12.7
    5000    12.3 5004.37    12.7 5006.51    14.3 5009.76    14.7 5023.98    21.2
 5033.44    24.2 5046.22    25.4 5089.73    25.7 5781.39   25.08 5946.01   27.12
 6200.43   26.79  6260.3   28.07 6559.61   28.38 7277.97   26.04 7442.59   27.29
 7726.94   26.22  7831.7   24.62 8116.05   24.45 8175.91   26.63 8475.23   25.34
#Mann= 3 ,-1 , 0
 1328.33     .07       0 4971.96     .03       0 5033.44     .07       0
#XS Ineff= 2 , 0
       0 4968.01    24.8 5036.34       0    24.8
Permanent Ineff=
       F       F
#Block Obstruct= 2 , 0
       0                 7682.04       0    26.5
Bank Sta=4971.96,5033.44
XS Rating Curve= 0
Exp/Cntr=.5,.3

Type RM Length L Ch R = 1 ,10138.08,44.83,44.83,44.83
BEGIN DESCRIPTION:
Cross Section updated by Carl Ahrendt, P.E., April 2012
END DESCRIPTION:
XS GIS Cut Line= 4
 3183416.973807213829059.7772968 3186846.713886113829193.5672279
 3187279.5757554 13829204.464491  3190557.416742 13829339.059895
#Sta/Elev= 30
 1337.04   25.97 1367.02   24.21 1426.97   25.96 1696.76    26.1 3255.56   23.78
 3270.55    25.1 3315.51   23.72  3330.5   24.96 4124.89   24.32 4409.67   25.72
  4754.4   22.88 4768.93    24.2 4972.02    19.8 4977.68    15.7    5000    12.2
 5030.95    14.6 5045.55    20.1  5095.2    22.9 5202.93    23.6 5217.37    21.6
 5292.27   23.01 5337.21   26.18 5412.11   23.19 5681.75   23.55 5981.34   25.65
  6086.2   24.53 6400.78   27.33 6505.64   26.11 6865.16   28.97 8482.99   25.92
#Mann= 3 ,-1 , 0
 1337.04     .07       0 4972.02     .04       0 5045.55     .07       0
#XS Ineff= 2 , 0
       0 4394.68   25.67 5352.19       0   26.21
Permanent Ineff=
       F       F
Bank Sta=4972.02,5045.55
XS Rating Curve= 0
Exp/Cntr=.3,.1

Type RM Length L Ch R = 1 ,10093.25,640.92,612.92,550.46
BEGIN DESCRIPTION:
Cross Section updated by Carl Ahrendt, P.E., April 2012
END DESCRIPTION:
XS GIS Cut Line= 4
 3183411.850188413829093.2542362 3187037.451511713829241.1602802
 3187151.727484313829246.6071466 3188899.007248113829301.9207723
#Sta/Elev= 30
 1299.26   25.46 1344.24   23.89 1524.17   25.54 3218.53   24.17 3248.52   24.95
  3278.5   23.58 3443.44   24.57 4598.01   24.35 4807.93   22.69 4950.56    18.5
 4976.15    15.6 4981.64    13.2    5000   11.83 5003.43    12.1 5019.22      21
 5042.54    22.7 5161.82   21.91 5236.53   24.19 5281.35   23.53 5326.18    26.1
    5371   23.55  5804.3   24.87 5998.54   26.76 6357.14   26.34 6401.96   25.89
  6416.9   24.69 6521.49   26.56 6611.14   26.07 6655.96   27.43 6790.44   27.48
#Mann= 3 ,-1 , 0
 1299.26     .07       0 4950.56     .04       0 5019.22     .07       0
#XS Ineff= 2 , 0
       0                 5326.18       0    26.1
Permanent Ineff=
       F       F
Bank Sta=4950.56,5019.22
XS Rating Curve= 0
Exp/Cntr=.3,.1

Type RM Length L Ch R = 1 ,9480.332,12.37,12.37,12.37
BEGIN DESCRIPTION:
Railroad Bridge
Cross Section updated by Carl Ahrendt, P.E., April 2012
END DESCRIPTION:
XS GIS Cut Line= 6
      3183392.99     13829489.94     3186223.448    13829511.802
     3186718.071    13829922.955     3187760.026    13829606.431
      3188485.48    13829507.229      3190036.21    13829529.857
#Sta/Elev= 30
 1237.52   25.61 1269.16   24.35 1305.99   25.46 1635.41   27.01 1870.62   24.71
 2676.64   25.35 3069.21   23.88 3097.55   24.95 3154.71   23.57 3189.21   24.77
 3223.65   23.44 4490.29   25.64 4657.92   24.11 4700.44   20.78 4978.08    17.9
 4989.29    14.6  4990.8    10.9    5000    10.7 5006.54    11.4 5016.08    17.3
 5041.88    19.7 5195.61    22.6 5772.21   24.23 5845.46   26.98 6035.15   24.72
 6897.83   25.44 7016.49   26.99 7126.79   24.75  7627.8   24.42 8083.12   26.51
#Mann= 5 ,-1 , 0
 1237.52     .07       0 1305.99     .12       0 3154.71     .07       0
 4978.08     .04       0 5016.08     .07       0
#XS Ineff= 2 , 0
       0 4490.29   25.64               0
Permanent Ineff=
       F       F
#Block Obstruct= 7 ,-1
                                                  5912.5 6173.42      25
 6244.93 6941.84   25.57  7016.5 8184.06   26.96    7030 8110.69    27.8
 5871.87 6234.93   25.63
Bank Sta=4978.08,5016.08
XS Rating Curve= 0
Exp/Cntr=.5,.3

Type RM Length L Ch R = 1 ,9467.966,33.13,33.13,33.13
BEGIN DESCRIPTION:
Railroad Bridge
Cross Section updated by Carl Ahrendt, P.E., April 2012
END DESCRIPTION:
XS GIS Cut Line= 6
       3183388.4    13829511.124      3186226.25    13829533.056
     3186716.601    13829933.993     3187762.024    13829616.251
     3188486.161    13829517.229     3190035.916    13829539.853
#Sta/Elev= 30
  1241.6   25.43 1277.83   24.27 1310.06   25.64 1639.62   27.08 1892.45   24.64
 2177.21   25.88 2246.29   24.43 3226.91   23.58 4494.71   25.58 4652.44   24.14
 4690.25   21.02  4817.6   22.66 4942.32   19.27  4949.6   21.17 4974.28    20.6
  4982.6    18.7 4992.99    12.2    5000    11.2 5011.45    12.1 5028.75    21.9
 5044.01   23.49  5178.9   22.15 5779.96   24.25 5848.08   26.96 6101.88   24.64
 6902.34   25.53  7011.6   27.13 7127.34      25  7623.3   24.23 8087.51   26.53
#Mann= 5 ,-1 , 0
  1241.6     .07       0 1310.06     .12       0 3226.91     .07       0
 4974.28     .04       0 5028.75     .07       0
#XS Ineff= 2 ,-1
  1241.6    4961    24.3    5039    5857    23.7
Permanent Ineff=
       F       F
#Block Obstruct= 5 ,-1
                            5858    6431      26  6438.5 7000.85   25.73
 7013.87 8222.69   27.08    7062 8108.06    27.8
Bank Sta=4974.28,5028.75
XS Rating Curve= 0
Exp/Cntr=.5,.3

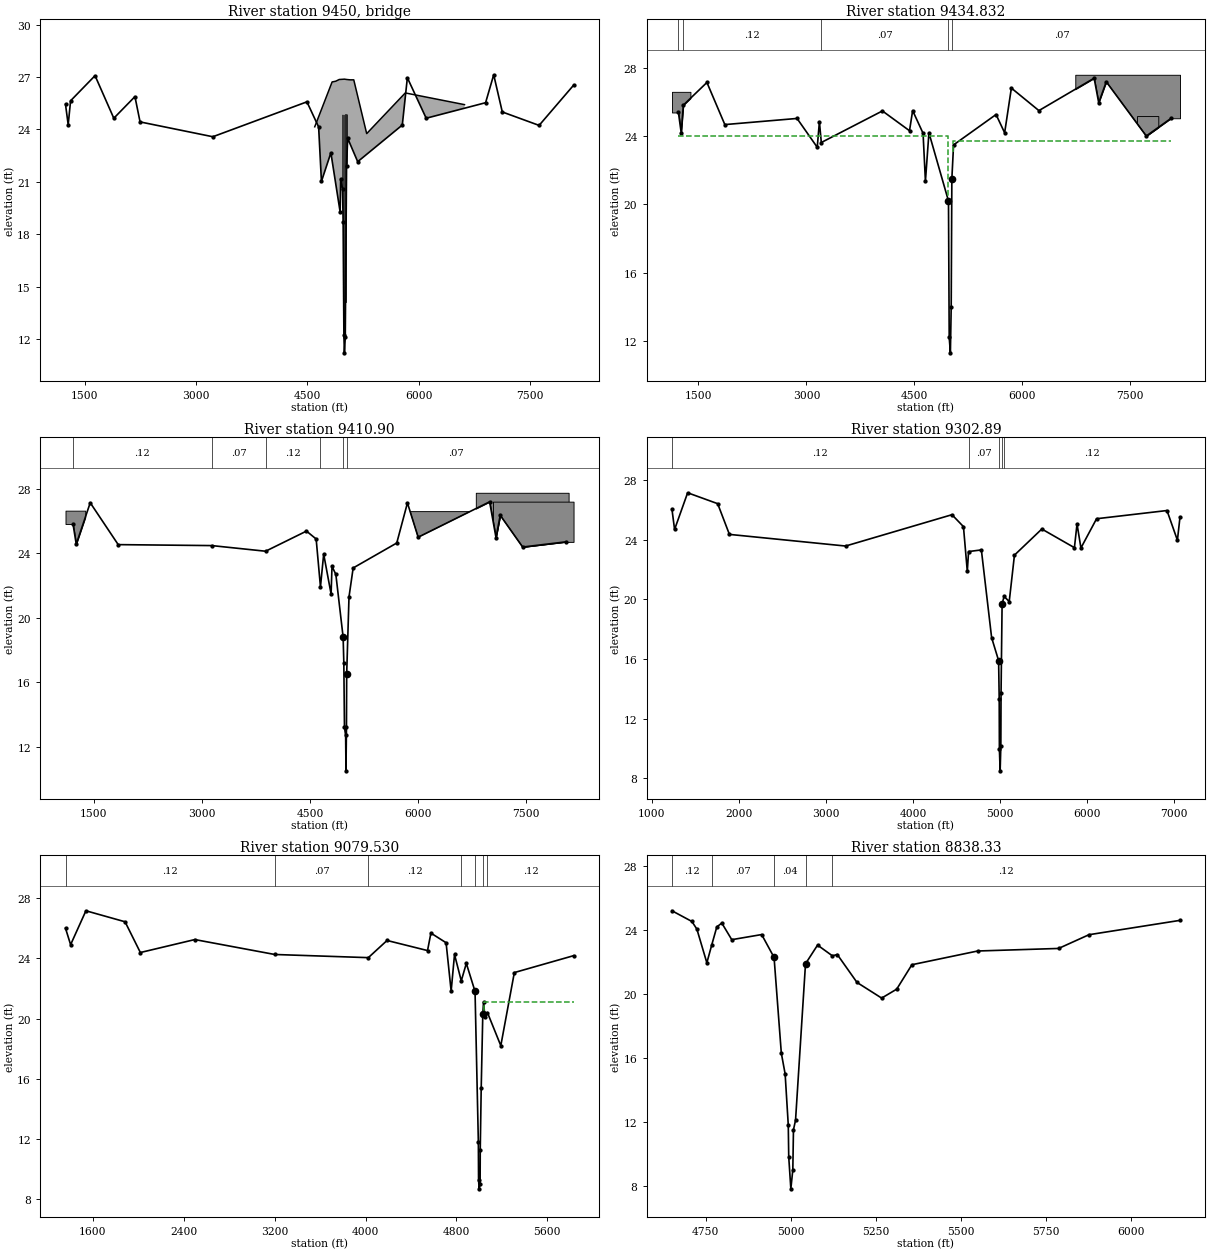
Type RM Length L Ch R = 3 ,9450    ,,,
BEGIN DESCRIPTION:
Railroad Bridge
END DESCRIPTION:
Bridge Culvert--1,0,-1,-1, 0
Deck Dist Width WeirC Skew NumUp NumDn MinLoCord MaxHiCord MaxSubmerge Is_Ogee
8,14,2.6,0, 14, 14, , , .95, 0, 0,0,,
    4600    4834    4882    4930    4969    4969    5000    5031    5031    5078
    5126    5300    5820    6618
   24.15   26.72   26.76   26.86   26.87   26.87   26.88   26.86   26.86   26.84
   26.84   23.76   26.09   25.42
       0       0       0       0       0   24.88   24.88   24.88       0       0
       0       0       0       0
    4600    4834    4882    4930    4969    4969    5000    5031    5031    5078
    5126    5300    5820    6618
   24.15   26.72   26.76   26.86   26.87   26.87   26.88   26.86   26.86   26.84
   26.84   23.76   26.09   25.42
       0       0       0       0       0   24.88   24.88   24.88       0       0
       0       0       0       0
Pier Skew, UpSta & Num, DnSta & Num=  ,4970, 2 ,4970, 2 , 0 , 0 , 0 ,,
       1       1
       0      25
       1       1
       0      25
Pier Skew, UpSta & Num, DnSta & Num=  ,4985, 2 ,4985, 2 , 0 , 0 , 0 ,,
       1       1
       0      25
       1       1
       0      25
Pier Skew, UpSta & Num, DnSta & Num=  ,5000, 2 ,5000, 2 , 0 , 0 , 0 ,,
       1       1
       0      25
       1       1
       0      25
Pier Skew, UpSta & Num, DnSta & Num=  ,5015, 2 ,5015, 2 , 0 , 0 , 0 ,,
       1       1
       0      25
       1       1
       0      25
Pier Skew, UpSta & Num, DnSta & Num=  ,5030, 2 ,5030, 2 , 0 , 0 , 0 ,,
       1       1
       0      25
       1       1
       0      25
BR Coef=-1 , 0 , 0 ,, 0 ,,,.8,-1,2,0,
WSPro=,,,, 1 ,,,, 0 ,,,, 0 ,,,,-1 ,-1 ,-1 , 0 , 0 , 0 , 0 , 0
BC Design=,, 0 ,, 0 ,,,,,,
BC HTab HWMax=27.13

Type RM Length L Ch R = 1 ,9434.832,23.93,23.93,23.93
BEGIN DESCRIPTION:
Railroad Bridge
Cross Section updated by Carl Ahrendt, P.E., April 2012
END DESCRIPTION:
XS GIS Cut Line= 6
      3183385.91    13829533.506      3186226.49    13829551.454
     3186739.561    13829976.452     3187768.097    13829663.187
     3188486.996    13829592.364     3190025.253    13829618.108
#Sta/Elev= 30
 1221.39   25.39  1260.1    24.2 1289.84   25.82  1617.3   27.15 1866.15   24.68
 2869.31   25.04 3150.14   23.35 3180.14   24.85 3206.53   23.63 4055.32   25.48
 4431.93   24.32 4475.44    25.5 4620.28   24.17    4653   21.36  4701.8    24.2
 4973.47    20.2 4983.43    12.2    5000    11.3 5011.14      14 5020.26    21.5
 5044.01   23.49 5634.22   25.27 5753.62    24.2  5847.1   26.82 6229.64    25.5
 6997.08    27.4 7060.64   25.96 7165.64   27.19 7721.48   24.01  8066.7   25.05
#Mann= 5 ,-1 , 0
 1221.39     .07       0 1289.84     .12       0 3206.53     .07       0
 4973.47     .04       0 5020.26     .07       0
#XS Ineff= 2 , 0
       0    4961      24    5039       0    23.7
Permanent Ineff=
       F       F
#Block Obstruct= 5 ,-1
 1131.79 1388.24    26.6    6735 8190.09    27.6 7592.82 7888.34   25.18
Bank Sta=4973.47,5020.26
XS Rating Curve= 0
Exp/Cntr=.5,.3

Type RM Length L Ch R = 1 ,9410.90 ,50.52,108.01,156.67
BEGIN DESCRIPTION:
Railroad Bridge
Cross Section updated by Carl Ahrendt, P.E., April 2012
END DESCRIPTION:
XS GIS Cut Line= 6
      3183389.62     13829543.16      3186228.34     13829561.35
      3186746.96     13829987.97      3187773.06     13829675.59
      3188484.76     13829601.79      3190025.44     13829632.12
#Sta/Elev= 30
 1209.41   25.83 1254.23   24.58 1448.47   27.15 1836.93   24.55  3136.8   24.49
 3883.86   24.14 4451.45   25.39 4585.86    24.9  4645.6   21.93  4690.4   23.96
  4793.4   21.48 4805.93    23.2 4859.39    22.7 4960.54    18.8 4970.19    17.2
    4979    13.2 4995.27    12.7    5000    10.5 5006.78    13.2  5009.8    16.5
 5041.93    21.3 5099.73    23.1 5705.16   24.65 5853.56   27.14 6002.54   25.01
 6994.89   27.21 7083.23   24.99 7142.12   26.37 7453.27    24.4 8050.11   24.72
#Mann= 6 ,-1 , 0
 1209.41     .12       0  3136.8     .07       0 3883.86     .12       0
  4645.6     .07       0 4960.54     .04       0  5009.8     .07       0
#Block Obstruct= 7 ,-1
 1105.13 1379.04   26.66 5677.02 5803.57    24.2 5867.14  7035.6    26.6
    6803 8091.61   27.77 7041.48 8160.25   27.22
Bank Sta=4960.54,5009.8
XS Rating Curve= 0
Exp/Cntr=.3,.1

Type RM Length L Ch R = 1 ,9302.89 ,147.05,223.36,269.2
BEGIN DESCRIPTION:
Cross Section updated by Carl Ahrendt, P.E., April 2012
END DESCRIPTION:
XS GIS Cut Line= 6
      3183392.26     13829570.37       3186222.3     13829583.61
      3186762.76     13830030.62 3186948.413545513829972.4112732
 3187006.352267413830032.5596091 3189021.722031113830189.3237409
#Sta/Elev= 30
 1230.72   26.04 1260.71   24.69 1410.65   27.15 1755.52   26.42 1890.47   24.36
 3224.98   23.58 4446.46   25.68 4578.62   24.88 4622.68   21.88 4637.36   23.21
 4784.28   23.32 4902.03   17.44  4982.3    15.9 4989.25    13.3 4991.21      10
    5000    8.51 5008.04    10.2 5010.31    13.7 5022.39    19.7 5045.34    20.2
 5104.32   19.86 5164.22   22.97 5478.67   24.72 5853.01   23.47 5882.96   25.06
 5927.88   23.45 6107.56   25.41 6916.14   25.96 7035.93   23.97 7065.87   25.53
#Mann= 5 ,-1 , 0
 1230.72     .12       0 4637.36     .07       0  4982.3     .04       0
 5022.39     .07       0 5045.34     .12       0
Bank Sta=4982.3,5022.39
XS Rating Curve= 0
Exp/Cntr=.3,.1

Type RM Length L Ch R = 1 ,9079.530,241.2,241.2,249.39
BEGIN DESCRIPTION:
Cross Section updated by Carl Ahrendt, P.E., April 2012
END DESCRIPTION:
XS GIS Cut Line= 6
 3183391.059731813829575.7945255 3186220.978358813829589.7178644
 3186781.886254913830052.9493735 3186835.636995513830198.6689941
 3186843.479047613830271.9812016 3187526.730750313830319.5256131
#Sta/Elev= 30
  1359.3   25.99 1404.22    24.9 1538.98   27.15 1883.37   26.42 2018.13   24.38
 2497.27   25.24 3201.02   24.25 4024.55   24.04 4189.25   25.18 4545.56   24.51
 4575.25   25.67 4708.87   25.03 4753.41   21.82  4783.1   24.25 4842.48    22.5
 4887.02   23.66 4963.68    21.8 4992.89    11.8 4994.64     9.3    5000     8.7
 5008.31       9 5009.54    11.3    5018    15.4 5031.98    20.3 5038.67    21.1
 5050.42    20.1 5072.53    20.4 5190.43    18.2 5309.54   23.05 5830.67   24.17
#Mann= 7 ,-1 , 0
  1359.3     .12       0 3201.02     .07       0 4024.55     .12       0
 4842.48     .07       0 4963.68     .04       0 5031.98     .07       0
 5072.53     .12       0
#XS Ineff= 2 , 0
                         5045.92           21.11
Permanent Ineff=
       F       F
Bank Sta=4963.68,5031.98
XS Rating Curve= 0
Exp/Cntr=.3,.1

Type RM Length L Ch R = 1 ,8838.33 ,59.56,59.56,59.56
BEGIN DESCRIPTION:
Cross Section updated by Carl Ahrendt, P.E., April 2012
END DESCRIPTION:
XS GIS Cut Line= 5
 3186545.366354813829883.3546003 3186590.937312713830157.7159299
 3186592.854750513830292.7841761 3186650.045692613830502.3973872
 3187510.473137713830553.9199887
#Sta/Elev= 30
 4650.79   25.22 4709.34   24.55 4723.98   24.07 4753.26   21.96 4767.89    23.1
 4782.53   24.21 4797.17   24.45 4826.44   23.41 4914.27   23.73  4950.7    22.3
 4972.02    16.3 4983.22      15 4992.43    11.8  4993.8     9.8    5000     7.8
 5005.81       9 5007.68    11.5 5013.79    12.1 5043.08    21.9 5078.48   23.07
 5121.93    22.4 5136.42   22.48 5194.36   20.73 5266.78   19.75 5310.99   20.31
 5355.57   21.84 5548.77    22.7 5786.56   22.86 5875.73   23.72 6143.24   24.62
#Mann= 5 ,-1 , 0
 4650.79     .12       0 4767.89     .07       0  4950.7     .04       0
 5043.08     .07       0 5121.93     .12       0
#XS Ineff= 2 , 0
       0 4782.53   24.21 5136.42       0   22.48
Permanent Ineff=
       F       F
Bank Sta=4950.7,5043.08
XS Rating Curve= 0
Exp/Cntr=.3,.1