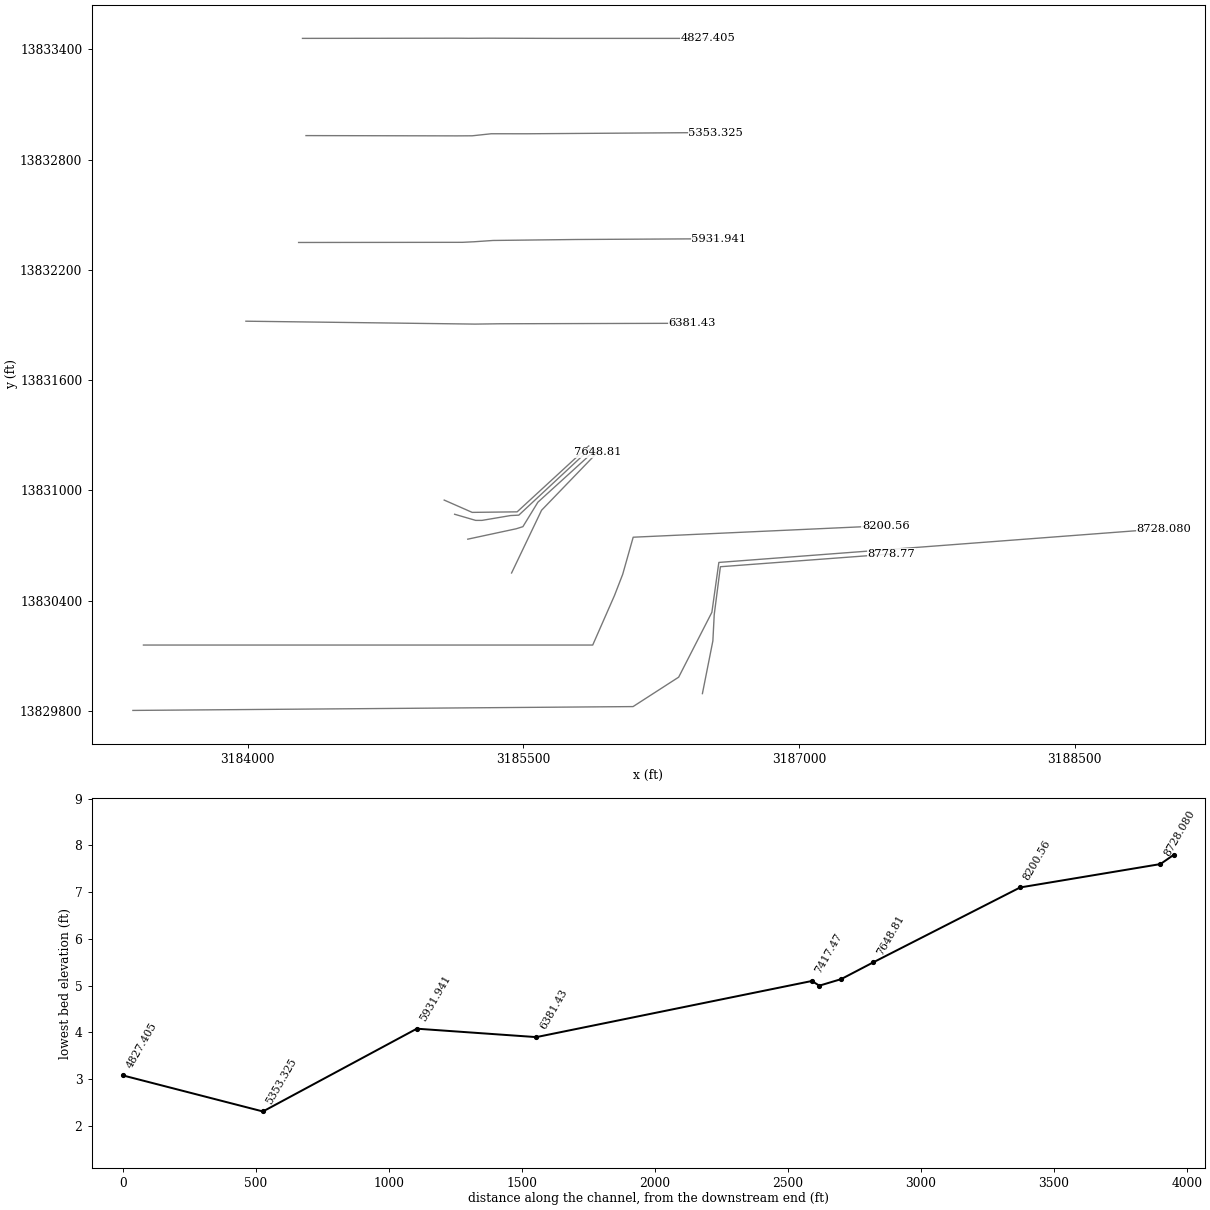
HEC-RAS study G108-00-00.prj: G108-00-00

--- G108-00-00.g01 (geometry) --- (continued)

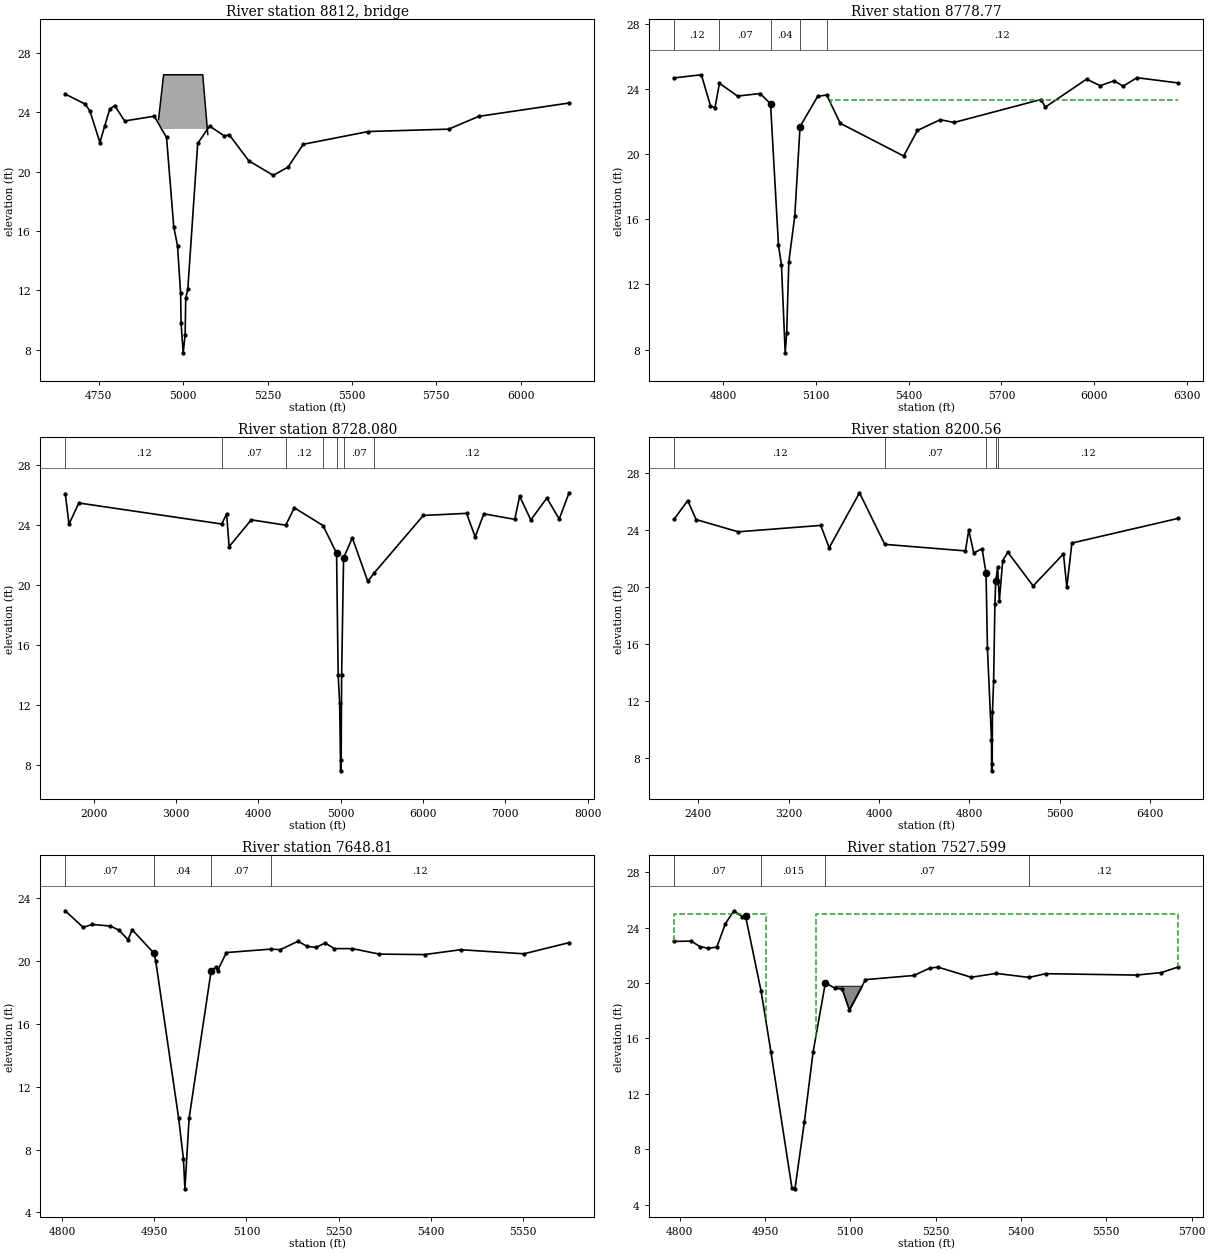
Type RM Length L Ch R = 3 ,8812    ,,,
BEGIN DESCRIPTION:
Pipe Crossing
END DESCRIPTION:
Bridge Culvert--1,0,-1,-1, 0
Deck Dist Width WeirC Skew NumUp NumDn MinLoCord MaxHiCord MaxSubmerge Is_Ogee
20,7.5,2.6,0, 5, 5, , , .95, 0, 0,0,,
    4927    4942    5058  5070.5    5073
    23.5   26.52   26.52   23.16    22.5
   22.87   22.87   22.87    20.5    20.5
    4927    4942    5058  5070.5    5073
    23.5   26.52   26.52   23.16    22.5
   22.87   22.87   22.87    20.5    20.5
BR Coef=-1 , 0 , 0 ,, 0 ,,,.8,-1,2,0,
WSPro=,,,, 1 ,,,, 0 ,,,, 0 ,,,,-1 ,-1 ,-1 , 0 , 0 , 0 , 0 , 0
BC Design=,, 0 ,, 0 ,,,,,,
BC HTab HWMax=27.47

Type RM Length L Ch R = 1 ,8778.77 ,67.26,50.69,28.74
BEGIN DESCRIPTION:
Cross Section updated by Carl Ahrendt, P.E., April 2012
END DESCRIPTION:
XS GIS Cut Line= 5
 3186474.868847513829894.4306895 3186531.812405513830181.4287423
 3186539.133378513830323.4904368 3186572.761790413830584.8335496
 3187502.744747513830654.3890616
#Sta/Elev= 30
 4640.83   24.69 4728.61   24.88 4757.87   22.99  4772.5   22.84 4787.13   24.36
 4845.64   23.57 4918.79   23.73 4952.52    23.1 4978.28    14.4 4987.89    13.2
    5000     7.8 5004.81       9 5011.78    13.4 5031.04    16.2 5048.09    21.7
 5104.95   23.55 5134.23   23.64 5178.14    21.9 5383.58   19.89 5427.99   21.46
    5502   22.12 5546.41   21.95 5827.67   23.36 5842.47    22.9 5975.69   24.61
  6020.1   24.21 6064.51   24.51 6094.12   24.18 6138.53    24.7 6271.75   24.38
#Mann= 5 ,-1 , 0
 4640.83     .12       0 4787.13     .07       0 4952.52     .04       0
 5048.09     .07       0 5134.23     .12       0
#XS Ineff= 2 , 0
       0 4787.13   24.36 5148.87       0   23.34
Permanent Ineff=
       F       F
Bank Sta=4952.52,5048.09
XS Rating Curve= 0
Exp/Cntr=.3,.1

Type RM Length L Ch R = 1 ,8728.080,527.52,527.52,527.52
BEGIN DESCRIPTION:
Cross Section updated by Carl Ahrendt, P.E., April 2012
END DESCRIPTION:
XS GIS Cut Line= 6
 3183375.366940313829802.9855596  3186097.379691 13829823.870568
 3186345.679234313829983.9889651  3186526.43145813830337.0177927
 3186564.362222413830608.2526506 3188987.349515513830792.3017864
#Sta/Elev= 30
 1656.38   26.06 1701.25   24.03  1820.9   25.44 3555.86   24.04 3615.69   24.71
  3645.6   22.53 3914.82   24.32  4333.6   23.96 4437.56   25.12 4785.46   23.94
 4950.73    22.1 4969.88      14 4988.19    12.1    5000     7.6 5006.52     8.3
 5012.21      14 5036.07    21.8 5142.62   23.11    5330   20.22 5404.42   20.76
 6004.41   24.61  6529.4   24.75  6634.4   23.18  6739.4   24.72 7114.39   24.35
 7174.39   25.89 7309.39   24.31 7504.39   25.77 7654.39   24.37 7774.39   26.12
#Mann= 7 ,-1 , 0
 1656.38     .12       0 3555.86     .07       0  4333.6     .12       0
 4785.46     .07       0 4950.73     .04       0 5036.07     .07       0
 5404.42     .12       0
#XS Ineff= 2 , 0
                         5142.86           23.09
Permanent Ineff=
       F       F
Bank Sta=4950.73,5036.07
XS Rating Curve= 0
Exp/Cntr=.3,.1

Type RM Length L Ch R = 1 ,8200.56 ,551.75,551.75,551.75
BEGIN DESCRIPTION:
Cross Section updated by Carl Ahrendt, P.E., April 2012
END DESCRIPTION:
XS GIS Cut Line= 6
 3183432.769650113830158.7591576 3185877.936316813830158.7591576
 3185996.5634932 13830428.779126 3186041.030056513830543.5260426
 3186098.113887313830745.4772062      3187472.38     13830808.21
#Sta/Elev= 30
 2187.92   24.78  2307.2   26.07 2381.74   24.74 2754.48   23.88 3485.05   24.33
  3559.6   22.76 3827.97   26.62 4051.61      23 4765.81   22.54  4795.3      24
 4839.54    22.4 4913.27   22.69 4948.34      21  4960.8    15.7  4996.7     9.3
 4997.91     7.1 5003.08     7.6 5005.12    11.2 5015.54    13.4 5027.02    18.8
 5033.76    20.4 5051.28    21.4 5066.07   19.02 5096.05   21.85 5141.02   22.45
 5365.36   20.08 5633.87   22.33  5663.7   19.99 5708.45   23.09 6648.22   24.82
#Mann= 5 ,-1 , 0
 2187.92     .12       0 4051.61     .07       0 4948.34     .04       0
 5033.76     .07       0 5051.28     .12       0
#XS Ineff= 2 , 0
       0                 5141.02       0   22.45
Permanent Ineff=
       F       F
Bank Sta=4948.34,5033.76
XS Rating Curve= 0
Exp/Cntr=.3,.1

Type RM Length L Ch R = 1 ,7648.81 ,173.48,121.21,51.5
XS GIS Cut Line= 3
     3185436.258     13830550.79      3185599.39     13830892.04
     3185904.964     13831208.65
#Sta/Elev= 30
 4805.47   23.21 4834.59   22.15 4849.15   22.34 4878.28   22.24 4892.84   21.98
  4907.4   21.37 4914.32      22  4949.8    20.5  4952.6      20  4989.8      10
  4997.6     7.4    5000     5.5  5006.8      10  5042.7    19.4 5049.82    19.6
 5053.01    19.4 5067.58   20.55 5140.38   20.77 5154.94   20.73 5184.07   21.27
 5198.76   20.94 5213.44   20.88 5228.13   21.16 5242.82    20.8  5272.2    20.8
 5316.26   20.45  5389.7   20.42 5448.46   20.73 5551.28   20.47 5624.72   21.18
#Mann= 4 ,-1 , 0
 4805.47     .07       0  4949.8     .04       0  5042.7     .07       0
 5140.38     .12       0
#Block Obstruct= 1 ,-1
 5049.82 5055.58    19.6
Bank Sta=4949.8,5042.7
XS Rating Curve= 0
Exp/Cntr=.5,.3

Type RM Length L Ch R = 1 ,7527.599,81.93,82.01,79.36
XS GIS Cut Line= 5
  3185197.86895713830734.8352064 3185461.3730399 13830791.402659
 3185497.891268813830802.8593582  3185579.52025113830936.0434871
 3185891.715305813831219.5967938
#Sta/Elev= 30
 4790.38      23 4820.33   23.02  4835.3   22.63 4850.27    22.5 4865.24   22.59
 4880.22   24.27 4895.19   25.21 4910.16   24.78 4915.85    24.8 4943.12    19.4
 4960.45      15 4997.35    5.19 5002.65    5.14 5019.25      10 5034.45      15
 5056.05      20 5072.65   19.63  5085.4   19.58 5098.16   18.05 5126.56   20.24
 5211.77   20.54 5240.17   21.08 5254.37   21.14 5312.54   20.41 5356.17   20.69
 5414.34    20.4 5443.43   20.67  5603.4   20.57 5647.03   20.75 5676.11   21.15
#Mann= 4 ,-1 , 0
 4790.38     .07       0 4943.12    .015       0 5056.05     .07       0
 5414.34     .12       0
#XS Ineff= 2 , 0
       0 4951.09      25 5039.04       0      25
Permanent Ineff=
       F       F
#Block Obstruct= 1 ,-1
 5072.65 5126.56    19.8
Bank Sta=4915.85,5056.05
XS Rating Curve= 0
Exp/Cntr=.5,.3

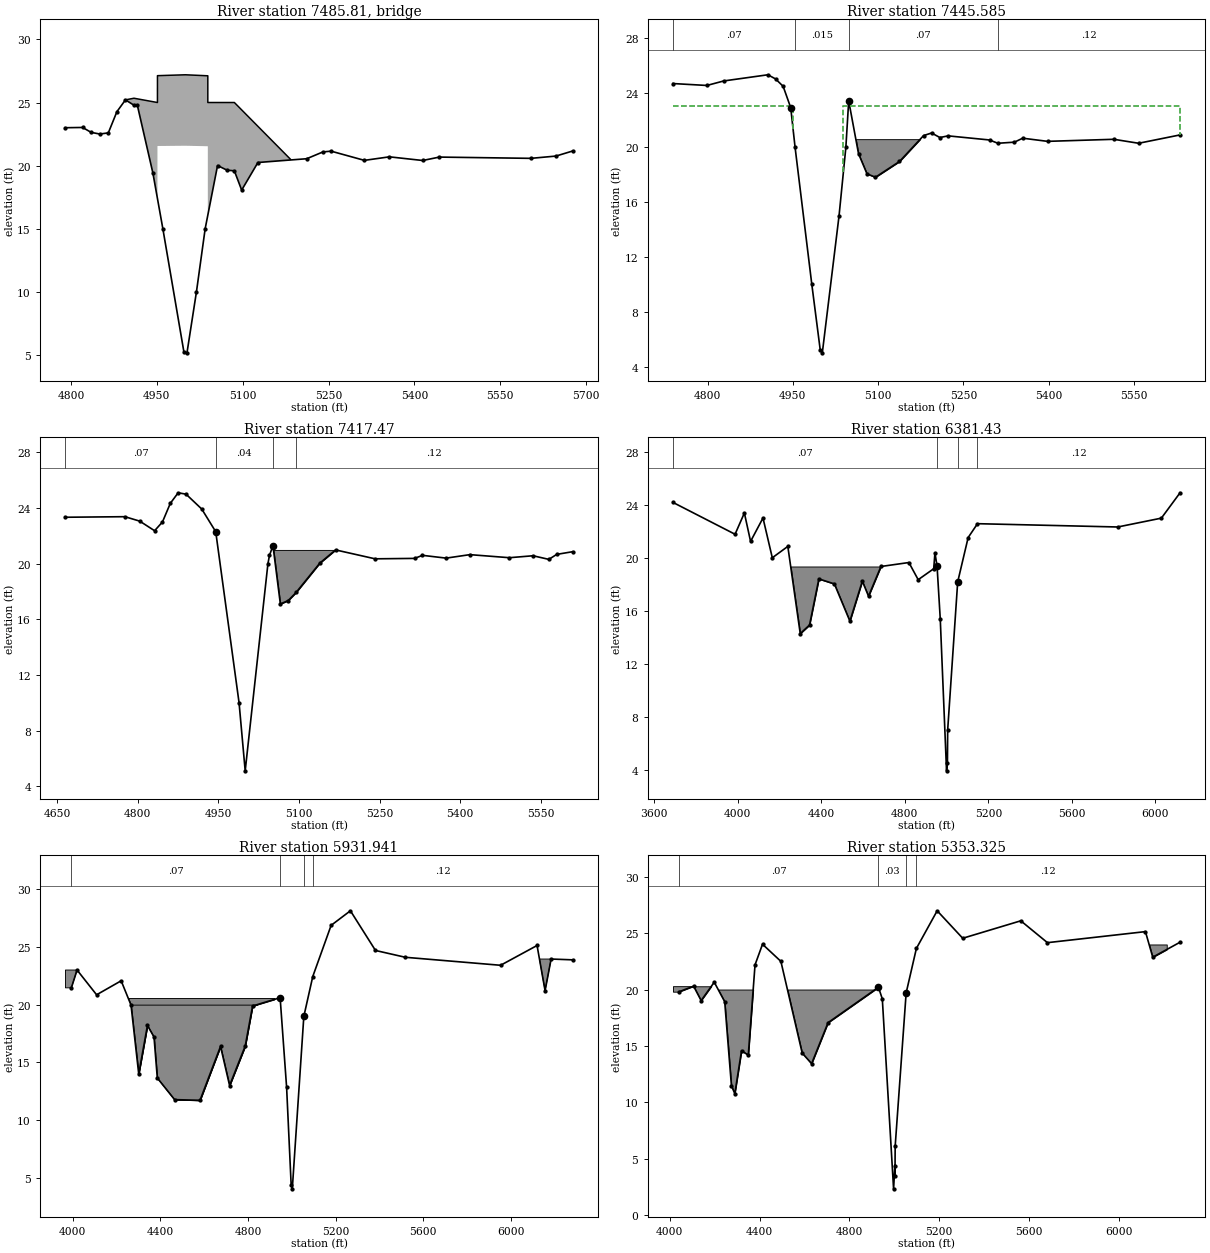
Type RM Length L Ch R = 3 ,7485.81 ,,,
BEGIN DESCRIPTION:
ACCESS ROAD
END DESCRIPTION:
Node Name=ACCESS ROAD
Bridge Culvert--1,0,-1,-1, 0
Deck Dist Width WeirC Skew NumUp NumDn MinLoCord MaxHiCord MaxSubmerge Is_Ogee
16.5,50,2.6,0, 9, 9, , , .95, 0, 0,0,,
 4895.19 4910.05 4951.05 4951.09    5000 5039.04 5039.05 5085.43 5183.37
   25.21   25.34      25   27.13    27.2   27.12      25      25    20.5
       0       0       0   21.55   21.57   21.53       0       0       0
 4895.19 4910.05 4951.05 4951.09    5000 5039.04 5039.05 5085.43 5183.37
   25.21   25.34      25   27.13    27.2   27.12      25      25    20.5
       0       0       0   21.55   21.57   21.53       0       0       0
BR Coef=-1 , 0 , 0 ,, 0 ,,,.8,-1,2,0,
WSPro=,,,, 1 ,,,, 0 ,,,, 0 ,,,,-1 ,-1 ,-1 , 0 , 0 , 0 , 0 , 0
BC Design=,, 0 ,, 0 ,,,,,,
BC HTab HWMax=25.21

Type RM Length L Ch R = 1 ,7445.585,29.25,28.12,19.47
XS GIS Cut Line= 6
 3185126.443597513830870.3464773 3185240.831579213830837.0504451
  3185275.20167713830837.0504451 3185430.941182513830863.3650512
 3185475.514903113830865.5131823 3185867.548830813831230.6954712
#Sta/Elev= 30
 4739.23   24.66  4798.8   24.52 4828.58   24.85 4906.14    25.3 4919.55      25
 4932.96   24.46  4946.3    22.9    4954      20  4983.4      10  4998.3    5.19
  5001.9       5  5031.3      15  5043.3      20  5048.3    23.4 5065.56   19.54
 5080.43   18.07 5095.31   17.82 5137.63   18.97 5179.96   20.86 5194.07   21.05
 5208.63   20.72  5223.2   20.84 5296.04   20.54 5310.61    20.3 5339.74   20.38
 5354.31   20.67 5398.01   20.44 5514.55   20.59 5558.25    20.3 5631.09   20.91
#Mann= 4 ,-1 , 0
 4739.23     .07       0    4954    .015       0  5048.3     .07       0
 5310.61     .12       0
#XS Ineff= 2 , 0
       0 4951.09      23 5039.04       0      23
Permanent Ineff=
       F       F
#Block Obstruct= 1 ,-1
 5050.68 5179.96    20.6
Bank Sta=4946.3,5048.3
XS Rating Curve= 0
Exp/Cntr=.5,.3

Type RM Length L Ch R = 1 ,7417.47 ,1036.04,1036.04,1036.04
XS GIS Cut Line= 4
     3185069.663     13830947.52     3185221.993     13830880.56
     3185466.625     13830883.57      3185856.42     13831242.13
#Sta/Elev= 30
 4665.67   23.34 4776.21   23.38 4803.84   23.06 4831.47   22.37  4846.1      23
 4860.72   24.34 4875.34    25.1 4889.96      25  4919.2   23.93  4945.2    22.3
  4988.6      10    5000     5.1  5042.3      20  5045.2    20.6 5051.67    21.3
 5065.42    17.1 5080.04   17.35 5094.73   17.93 5138.81   20.04 5168.19   20.99
 5241.65   20.35  5315.1   20.38 5329.79    20.6 5373.87    20.4 5417.94   20.65
  5491.4   20.43 5535.47   20.57 5564.85   20.31 5579.54   20.67 5608.93   20.86
#Mann= 4 ,-1 , 0
 4665.67     .07       0  4945.2     .04       0 5051.67     .07       0
 5094.73     .12       0
#Block Obstruct= 1 ,-1
 5051.67 5168.19   20.99
Bank Sta=4945.2,5051.67
XS Rating Curve= 0
Exp/Cntr=.3,.1

Type RM Length L Ch R = 1 ,6381.43 ,449.49,449.49,449.49
BEGIN DESCRIPTION:
Cross Section updated by Carl Ahrendt, P.E., April 2012
END DESCRIPTION:
XS GIS Cut Line= 4
 3183990.422784813831920.8756038 3185238.436775413831905.0978486
 3185373.420255913831906.8798342 3186417.650667713831909.5673901
#Sta/Elev= 30
 3690.45   24.22 3987.62   21.81  4032.2   23.42 4061.91   21.27 4121.35   23.04
 4165.92   20.03 4240.21   20.89 4299.65   14.29 4344.22   14.94  4388.8   18.43
 4463.09   18.05 4537.38   15.23 4596.82   18.26 4626.54   17.12 4685.97   19.37
  4819.7   19.67 4864.27   18.37 4938.59    19.2 4944.46    20.4  4954.6    19.4
 4969.88    15.4    5000     3.9 5004.23     4.5 5005.43       7 5053.32    18.2
  5103.4   21.56 5148.15   22.61 5819.44   22.36 6028.29   23.03  6117.8   24.95
#Mann= 4 ,-1 , 0
 3690.45     .07       0  4954.6     .03       0 5053.32     .07       0
 5148.15     .12       0
#Block Obstruct= 2 , 0
       0 4685.97   19.37               0
Bank Sta=4954.6,5053.32
XS Rating Curve= 0
Exp/Cntr=.3,.1

Type RM Length L Ch R = 1 ,5931.941,580.95,578.62,577.33
XS GIS Cut Line= 6
     3184277.306    13832349.233      3185168.73    13832350.054
     3185232.354    13832353.124      3185335.68    13832360.173
      3185786.25    13832365.411     3186565.033    13832369.623
#Sta/Elev= 30
 3993.24   21.45 4019.26   22.99 4108.48   20.85 4220.56   22.06 4265.56   19.96
 4300.78   14.01 4340.56    18.2 4370.56    17.2 4385.56   13.66 4464.48   11.79
 4580.56   11.73 4674.24   16.39 4715.56   13.01 4786.96   16.42 4820.56   19.88
  4946.3    20.6 4975.91   12.85 4996.82    4.37 5001.86    4.08  5054.5   18.98
 5095.36   22.43 5179.14   26.85 5267.18   28.11 5381.68   24.68 5518.32   24.09
 5952.84    23.4 6119.32   25.11 6155.92   21.21 6183.54   23.94 6281.32   23.87
#Mann= 4 ,-1 , 0
 3993.24     .07       0  4946.3     .03       0  5054.5     .07       0
 5095.36     .12       0
#Block Obstruct= 5 ,-1
 3966.26 4019.37   22.99    4223 4919.57   20.57
 4253.99 4853.28      20 6123.61 6193.31   23.94
Bank Sta=4946.3,5054.5
XS Rating Curve= 0
Exp/Cntr=.3,.1

Type RM Length L Ch R = 1 ,5353.325,531.34,525.92,517.66
XS GIS Cut Line= 6
     3184317.464    13832930.779      3185139.65    13832929.268
     3185221.779    13832929.679     3185325.996    13832940.841
     3185521.059    13832940.725     3186546.236    13832947.536
#Sta/Elev= 30
 4042.48   19.81 4106.14    20.3 4139.64   19.02 4198.08   20.65 4244.64   18.92
 4274.64   11.45 4289.64   10.76 4319.64   14.57 4349.64   14.18 4379.64   22.19
 4412.96   24.02 4494.74    22.5 4589.64   14.36 4631.46   13.42 4704.76   17.06
 4929.08    20.2  4946.3   19.17 4996.46    2.31 5002.38    4.38 5002.69    3.43
 5003.54    6.09 5052.41    19.7 5098.02   23.65 5190.52   26.99 5304.26   24.55
  5562.8    26.1 5681.42   24.16 6117.74   25.14 6150.26   22.87 6271.86    24.2
#Mann= 4 ,-1 , 0
 4042.48     .07       0 4929.08     .03       0 5052.41     .07       0
 5098.02     .12       0
#Block Obstruct= 5 ,-1
 4014.33 4105.82    20.3 4106.12 4198.52   20.29 4210.11 4388.82      20
 4510.15 4919.07      20    6126 6212.59      24
Bank Sta=4929.08,5052.41
XS Rating Curve= 0
Exp/Cntr=.3,.1

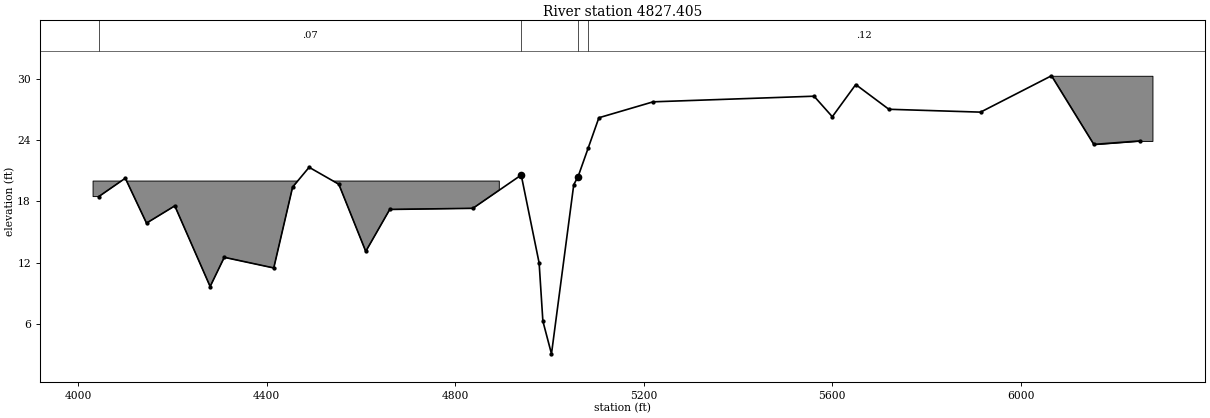
Type RM Length L Ch R = 1 ,4827.405,1628.1,1631.34,1638.19
XS GIS Cut Line= 6
     3184298.344     13833459.73      3185140.56    13833460.728
     3185203.101    13833460.219      3185305.96    13833460.773
     3185677.024     13833459.73     3186506.909     13833459.73
#Sta/Elev= 30
 4043.69   18.48 4099.97   20.28 4144.97   15.88 4204.97   17.57 4279.97    9.67
 4309.97   12.53 4414.97   11.49 4454.95   19.41 4489.97   21.35 4552.94   19.69
 4610.14   13.11 4661.03   17.22 4837.39   17.33 4939.95   20.59 4977.96   11.98
 4985.91    6.28 5004.17    3.08 5051.43   19.65 5060.57   20.43 5081.72   23.19
 5104.74    26.2 5219.93   27.76 5561.23   28.31 5599.98    26.3 5649.69   29.45
 5719.98   27.03 5914.55   26.75 6064.98   30.31 6154.76   23.59 6252.26   23.93
#Mann= 4 ,-1 , 0
 4043.69     .07       0 4939.95     .03       0 5060.57     .07       0
 5081.72     .12       0
#Block Obstruct= 2 ,-1
  4031.6 4893.47      20 6065.15 6279.19   30.31
Bank Sta=4939.95,5060.57
XS Rating Curve= 0
Exp/Cntr=.3,.1