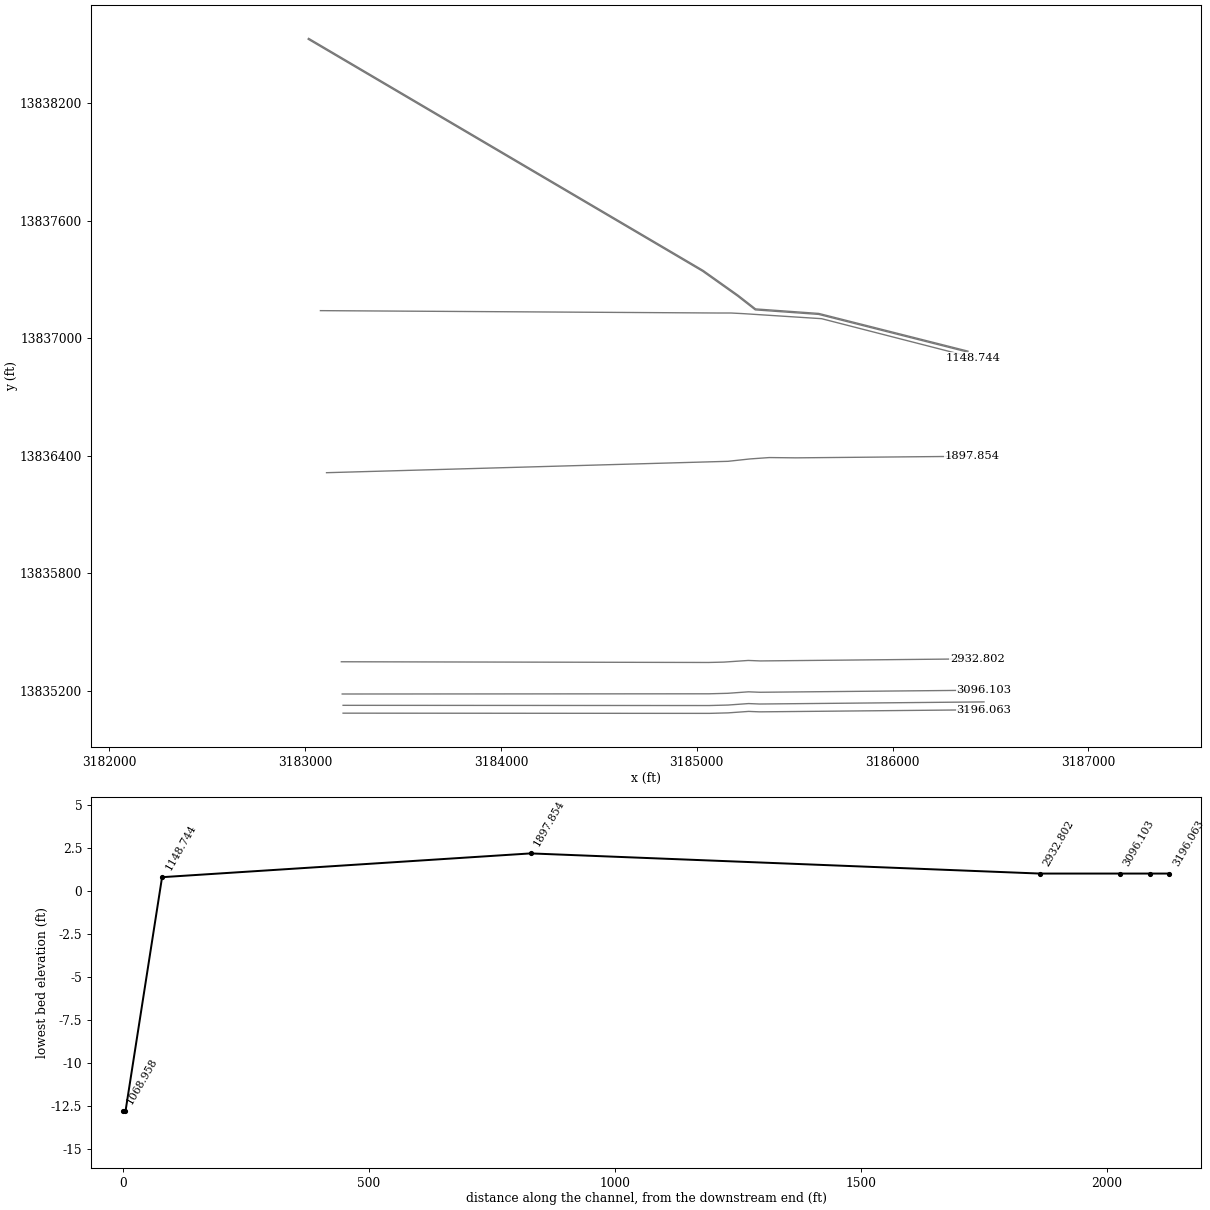
HEC-RAS study G108-00-00.prj: G108-00-00

--- G108-00-00.g01 (geometry) --- (continued)

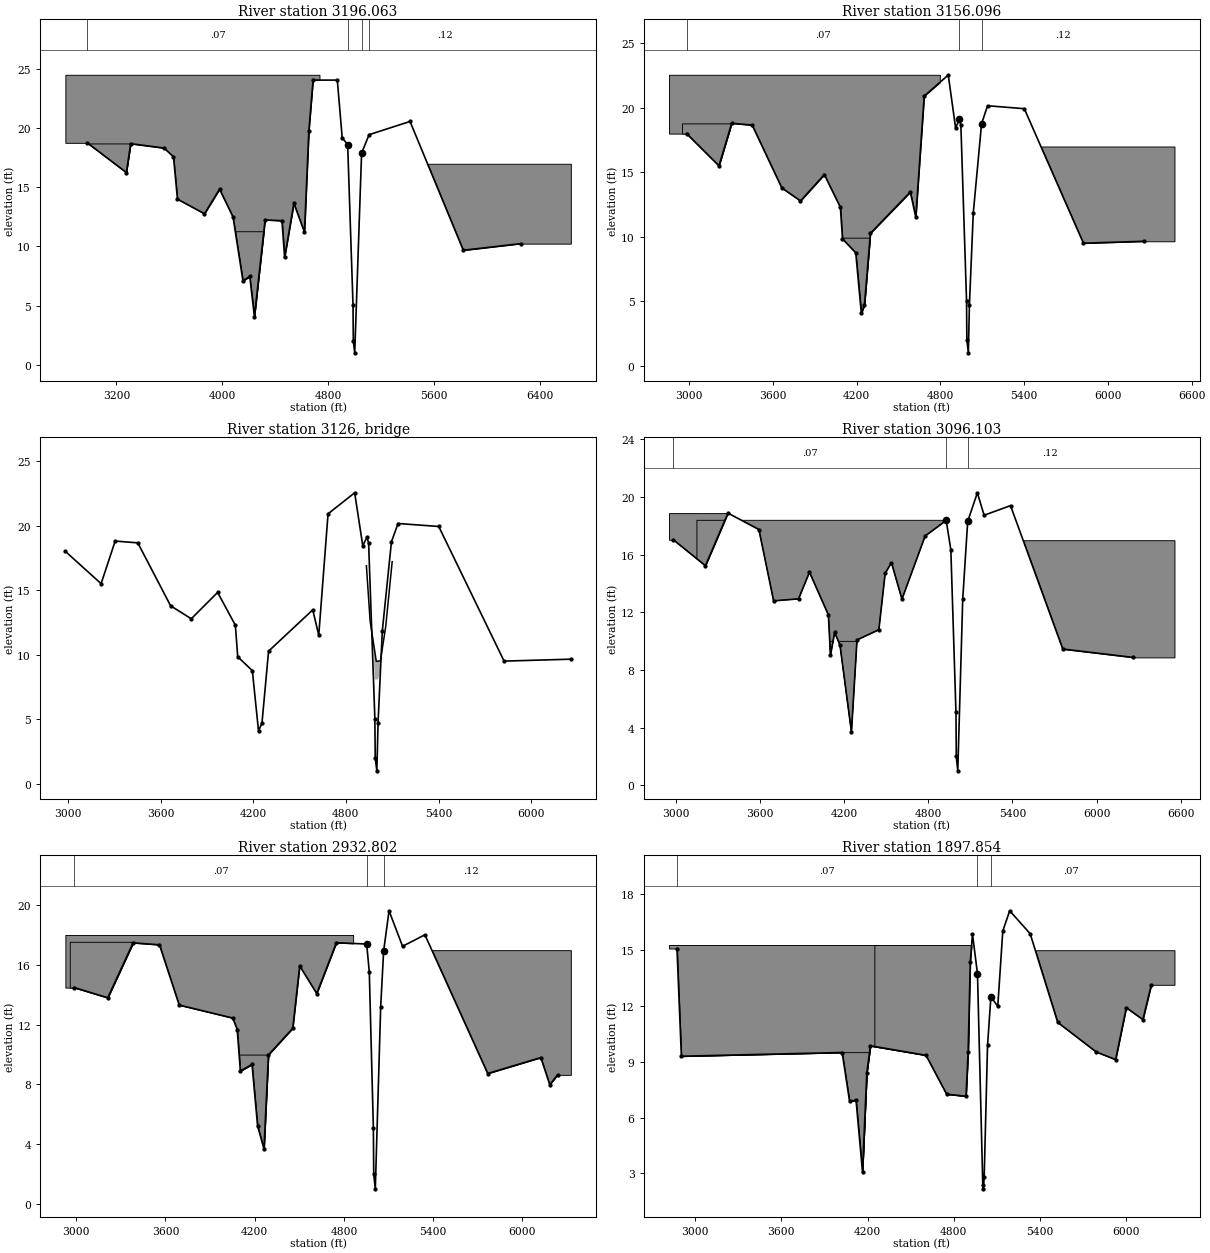
Type RM Length L Ch R = 1 ,3196.063,40.04,39.97,40
BEGIN DESCRIPTION:
Access Road
END DESCRIPTION:
XS GIS Cut Line= 6
     3183193.562    13835086.037     3185063.701    13835084.967
     3185160.026    13835087.505      3185265.08    13835095.005
     3185321.174    13835092.766     3186467.236    13835103.551
#Sta/Elev= 30
  2979.9   18.77 3274.76   16.26 3307.52    18.7 3559.86   18.33 3630.96   17.59
 3660.96   14.01  3865.3   12.77 3979.18   14.85 4080.96    12.5 4155.96     7.1
  4207.5    7.47 4242.68    4.07 4323.52   12.25 4450.92   12.18 4470.96    9.07
 4540.98   13.65 4620.96   11.21 4654.32    19.8    4686   24.08 4869.22   24.08
 4905.98    19.2 4947.34   18.63 4987.84    5.05 4990.15       2 5000.74       1
 5052.66    17.9 5109.15   19.46  5418.8   20.58 5821.34    9.68 6253.96   10.24
#Mann= 4 ,-1 , 0
  2979.9     .07       0 4947.34     .03       0 5052.66     .07       0
 5109.15     .12       0
#Block Obstruct= 4 ,-1
 2813.99 4734.36   24.53 2924.91 3305.57   18.72 4038.11 4338.45   11.29
 5419.24 6634.06      17
Bank Sta=4947.34,5052.66
XS Rating Curve= 0
Exp/Cntr=.5,.3

Type RM Length L Ch R = 1 ,3156.096,59.64,59.99,60
BEGIN DESCRIPTION:
Access Road
END DESCRIPTION:
XS GIS Cut Line= 6
     3183193.562    13835126.088     3185063.253    13835124.968
     3185159.372    13835127.511     3185264.795    13835135.048
     3185321.739    13835132.775     3186466.875     13835143.55
#Sta/Elev= 30
 2983.39      18 3214.77    15.5 3305.93    18.8  3452.5   18.66 3664.72   13.79
 3798.68   12.78 3969.34   14.82 4084.45   12.28 4099.45    9.84 4194.39    8.76
 4234.45    4.07    4257    4.74 4299.41   10.27 4585.45   13.47 4624.45   11.51
 4684.63   20.91    4857   22.54 4909.47   18.44 4937.24   19.11 4947.34   18.63
 4987.84    5.05 4990.15       2 5000.74       1 5008.53    4.74  5036.1   11.84
 5095.31   18.75 5138.08   20.16 5401.53   19.93 5824.84     9.5  6257.1    9.65
#Mann= 3 ,-1 , 0
 2983.39     .07       0 4937.24     .03       0 5095.31     .12       0
#XS Ineff= 3 ,-1
                            3500    4962       9    5036    5200       9
Permanent Ineff=
       F       F       F
#Block Obstruct= 4 ,-1
 2857.06 4796.78   22.56 2949.91 3304.98   18.79 4051.76  4352.1    9.93
 5230.37 6476.93      17
Bank Sta=4937.24,5095.31
XS Rating Curve= 0
Exp/Cntr=.5,.3

Type RM Length L Ch R = 3 ,3126    ,,,
BEGIN DESCRIPTION:
Access Road
END DESCRIPTION:
Bridge Culvert--1,0,-1,-1, 0
Deck Dist Width WeirC Skew NumUp NumDn MinLoCord MaxHiCord MaxSubmerge Is_Ogee
16,20,2.6,0, 6, 6, , , .95, 0, 0,0,,
    4933    4957    4997    5024    5058    5100
  16.888  12.621   9.482   9.526  12.169  17.202
    8.08    8.08    8.08    8.08    8.08    8.08
    4933    4957    4997    5024    5058    5100
  16.888  12.621   9.482   9.526  12.169  17.202
    8.08    8.08    8.08    8.08    8.08    8.08
BR Coef=-1 , 0 , 0 ,, 0 ,,,.8,-1,,0,
WSPro=,,,, 1 ,,,, 0 ,,,, 0 ,,,,-1 ,-1 ,-1 , 0 , 0 , 0 , 0 , 0
BC Design=,, 0 ,, 0 ,,,,,,
BC HTab HWMax=22.55

Type RM Length L Ch R = 1 ,3096.103,160.9,163.3,160.1
BEGIN DESCRIPTION:
Access Road
END DESCRIPTION:
XS GIS Cut Line= 6
     3183189.112    13835183.938     3185062.581    13835184.968
     3185158.391    13835187.521     3185264.368    13835195.113
     3185322.586    13835192.789     3186466.335    13835203.547
#Sta/Elev= 30
 2982.62   17.03 3211.55   15.23 3372.28   18.88 3592.69   17.74 3697.72   12.79
 3875.61   12.93 3953.36   14.78 4088.13   11.82 4103.13    9.02 4133.13    10.6
 4170.92    9.72 4252.62     3.7 4292.23   10.08 4448.13   10.79 4493.13    14.7
 4538.13   15.44 4612.81   12.91 4778.13   17.29 4928.15   18.37  4961.3   16.35
 4997.84    5.05 5000.15       2 5010.74       1  5046.1   12.91 5081.45    18.3
 5150.35   20.29 5198.49   18.73  5386.8    19.4 5759.34    9.45 6260.25    8.87
#Mann= 3 ,-1 , 0
 2982.62     .07       0 4928.15     .03       0 5081.45     .12       0
#XS Ineff= 3 ,-1
                            3000    4972       9    5046    5300       9
Permanent Ineff=
       F       F       F
#Block Obstruct= 4 ,-1
 2951.68 3371.18   18.88 3150.74 4907.28   18.38 4042.66 4470.42    9.98
 5312.16 6555.89      17
Bank Sta=4928.15,5081.45
XS Rating Curve= 0
Exp/Cntr=.5,.3

Type RM Length L Ch R = 1 ,2932.802,1017.72,1034.95,1035.49
BEGIN DESCRIPTION:
Access Road
END DESCRIPTION:
XS GIS Cut Line= 6
     3183184.662     13835348.59     3185060.789     13835344.97
     3185138.615     13835346.85      3185263.23    13835355.286
     3185324.846    13835352.826      3186432.38    13835363.695
#Sta/Elev= 30
 2987.69   14.49 3212.65   13.81 3383.15   17.49 3560.12   17.36 3692.66   13.32
 4052.66   12.45 4082.66   11.68  4103.9     8.9 4182.09    9.34 4219.63    5.22
 4262.66    3.67 4292.66    9.98 4455.89   11.76 4502.66   15.94 4617.28   14.09
 4749.31    17.5 4952.75   17.41  4970.4   15.54 4997.84    5.05 5000.15       2
 5010.74       1    5047   13.22 5066.72   16.94 5103.14   19.64 5194.03   17.26
 5344.15   18.03 5766.23    8.73 6123.21     9.8 6183.22    7.98 6235.97    8.64
#Mann= 3 ,-1 , 0
 2987.69     .07       0 4952.75     .03       0 5066.72     .12       0
#Block Obstruct= 4 ,-1
 2927.76 4861.77   18.02 2957.21 3397.62   17.56 4074.52  4333.9      10
 5344.76 6324.96      17
Bank Sta=4952.75,5066.72
XS Rating Curve= 0
Exp/Cntr=.3,.1

Type RM Length L Ch R = 1 ,1897.854,771.2,749.11,698.98
XS GIS Cut Line= 6
     3183109.011    13836314.249     3185159.222    13836372.365
     3185272.123    13836384.571     3185370.771    13836391.551
     3185506.579    13836390.093     3186408.407    13836398.254
#Sta/Elev= 30
 2874.02   15.09 2904.64     9.3 4023.58     9.5 4075.12    6.88 4120.14    6.94
 4165.16    3.08 4195.16     8.4 4220.22    9.86 4606.92    9.35 4750.38    7.26
 4885.44    7.15 4900.44    9.55 4915.46   14.38 4930.46   15.87 4965.32   13.73
 5002.08     2.4 5006.29    2.17 5011.92    2.79  5035.3    9.88  5058.6    12.5
 5106.52   11.98  5141.4   16.03 5189.38   17.12 5331.82   15.89 5523.62   11.12
  5791.8    9.53 5926.86    9.12    6001   11.91 6116.44   11.27 6175.22   13.14
#Mann= 3 ,-1 , 0
 2874.02     .07       0 4965.32     .03       0  5058.6     .07       0
#Block Obstruct= 5 ,-1
 2790.29 4921.17    11.2 2818.54    4279   15.28 4001.71 4261.09    9.52
 4247.63 4934.52   15.28 5193.97 6336.18      15
Bank Sta=4965.32,5058.6
XS Rating Curve= 0
Exp/Cntr=.3,.1

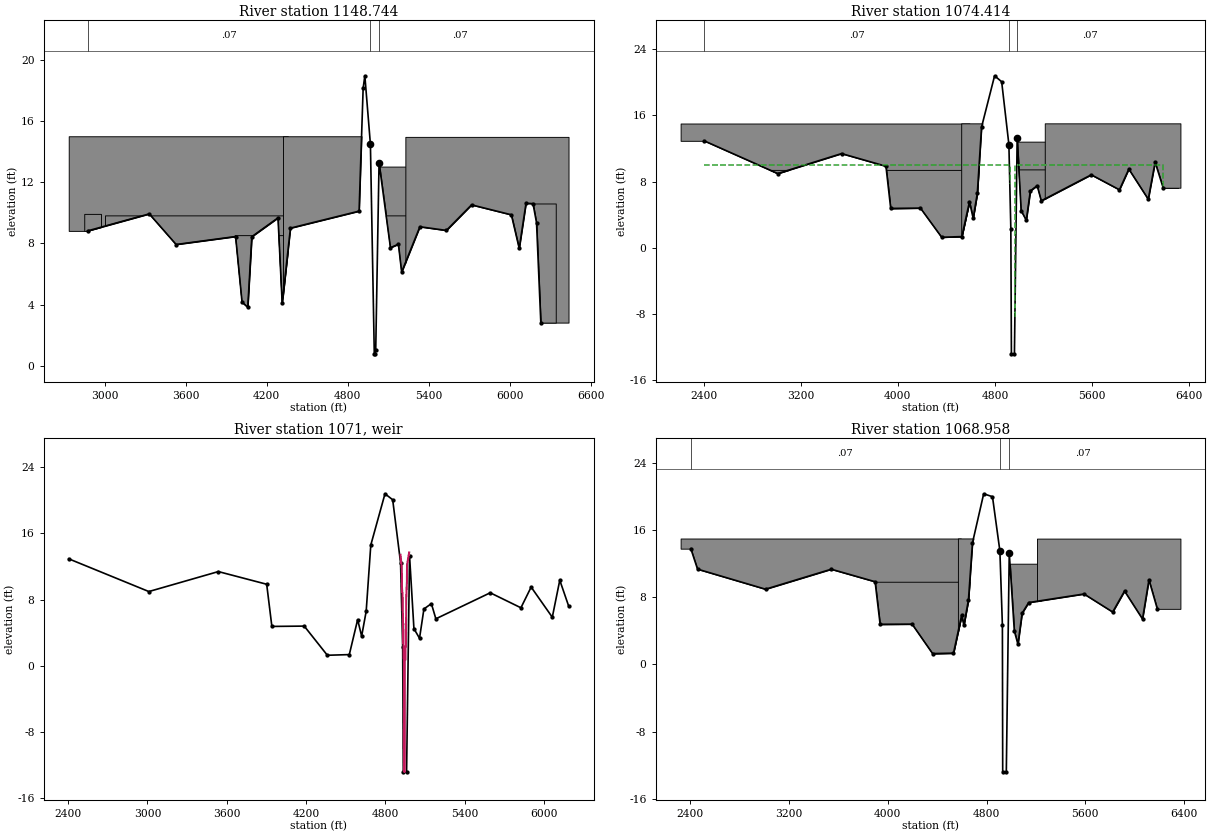
Type RM Length L Ch R = 1 ,1148.744,347.82,74.33,17.76
XS GIS Cut Line= 6
     3183077.861    13837141.957     3185109.495    13837129.854
     3185174.596    13837129.885     3185238.554    13837126.576
     3185637.527    13837100.889     3186410.424    13836902.624
#Sta/Elev= 30
 2872.36    8.82  3329.1    9.93 3528.14    7.93 3968.98    8.45 4016.66    4.17
 4059.16    3.83 4089.16    8.44  4283.2    9.67 4314.16    4.09 4375.24       9
 4884.16   10.11 4914.16   18.14  4926.7   18.95 4967.98   14.48 4996.74      .8
 5000.73     .79 5007.38    1.06 5032.02   13.27 5116.58    7.72 5175.56    7.95
 5199.62    6.13  5334.5    9.09 5530.72    8.85 5717.66   10.52 6012.72    9.87
 6070.84    7.68 6121.24   10.62 6173.02    10.6 6199.12    9.35  6230.9    2.83
#Mann= 3 ,-1 , 0
 2872.36     .07       0 4967.98    .015       0 5032.02     .07       0
#Block Obstruct= 9 ,-1
 2732.08    4356      15 2847.14 2971.08    9.93 3004.58 4869.96     9.8
  3965.3 4420.36    8.51 4319.81 4915.29      15 5032.43 5231.75   13.02
 5070.14 6138.73     9.8    5227 6436.29   14.96 6172.06 6341.52   10.61
Bank Sta=4967.98,5032.02
XS Rating Curve= 0
Exp/Cntr=.5,.3

Type RM Length L Ch R = 1 ,1074.414,5.7,5.46,5.03
BEGIN DESCRIPTION:
Weir
END DESCRIPTION:
XS GIS Cut Line= 6
     3183015.031    13838528.472     3185029.856    13837343.115
     3185207.884    13837216.729     3185298.793     13837145.85
     3185622.369    13837122.738     3186383.851    13836930.256
#Sta/Elev= 30
 2404.26   12.91 3010.42    8.96  3536.2   11.37  3901.9    9.84  3941.1    4.75
 4185.92    4.79 4360.84    1.27  4526.9    1.35 4589.98    5.57  4620.2    3.57
 4654.62    6.58 4689.44   14.57 4796.82   20.76  4855.1   20.04 4914.58   12.46
 4930.64    2.22  4935.3   -12.8 4960.21   -12.8 4982.68   13.27 5015.82    4.48
 5058.08    3.32 5091.42    6.86 5147.88     7.5 5181.66    5.67  5593.1    8.81
 5825.18       7 5902.54     9.5  6062.6    5.86 6119.14   10.33 6185.38    7.25
#Mann= 3 ,-1 , 0
 2404.26     .07       0 4914.58    .015       0 4982.68     .07       0
#XS Ineff= 2 , 0
       0    4922      10    4964       0      10
Permanent Ineff=
       F       F
#Block Obstruct= 7 ,-1
 2210.47    4589      15 2940.79 3490.32     9.4 3533.69 4685.06     9.4
  4521.7 4744.33   15.02 4983.48 5217.61   12.81 4990.22  6308.3     9.4
    5210 6327.58   15.02
Bank Sta=4914.58,4982.68
XS Rating Curve= 0
Exp/Cntr=.5,.3

Type RM Length L Ch R = 5 ,1071    ,,,
BEGIN DESCRIPTION:
Weir at mouth
END DESCRIPTION:
IW Pilot Flow=0
#Inline Weir SE= 19
    4914    13.4    4924   11.82    4925    9.45    4930     8.4    4933       5
    4935     5.1    4936    2.03    4940     .56    4940   -12.8    4946   -12.8
    4946      .5    4951     .75    4953    2.25    4955    2.28    4957    5.57
    4958    8.33    4963   10.16    4964   12.21    4980   13.68
IW Dist,WD,Coef,Skew,MaxSub,Min_El,Is_Ogee,SpillHt,DesHd
2,.33,3,0,.95,,-1 ,,,0,0,

Type RM Length L Ch R = 1 ,1068.958,86.83,1068.96,210.84
BEGIN DESCRIPTION:
Weir
END DESCRIPTION:
XS GIS Cut Line= 6
     3183017.567    13838532.781     3185032.576    13837347.316
     3185210.901    13837220.719     3185300.568    13837150.736
     3185623.166    13837127.694     3186385.076    13836935.104
#Sta/Elev= 30
  2403.4   13.79 2457.83   11.35 3008.69    8.96 3541.32   11.34 3896.56    9.85
 3937.28    4.78 4196.22     4.8  4362.4    1.29 4531.64    1.34 4597.61    5.84
 4616.01    4.68 4653.03    7.69 4685.63   14.49 4776.38   20.33 4847.67   19.98
 4907.64   13.52 4927.95    4.67 4930.48   -12.8 4959.69   -12.8 4983.55   13.27
 5024.65    3.99 5054.06    2.39 5087.82     6.1 5140.75    7.37 5589.47    8.39
 5821.55    6.24 5917.57    8.74 6063.23    5.41 6115.51   10.08 6183.02    6.62
#Mann= 3 ,-1 , 0
  2403.4     .07       0 4907.64    .015       0 4983.55     .07       0
#Block Obstruct= 5 ,-1
 2320.72    4591      15  3894.2 4730.38    9.85 4567.51 4732.27   15.01
 4985.48 5240.42      12    5208 6370.46   14.99
Bank Sta=4907.64,4983.55
XS Rating Curve= 0
Exp/Cntr=.5,.3

Chan Stop Cuts=-1